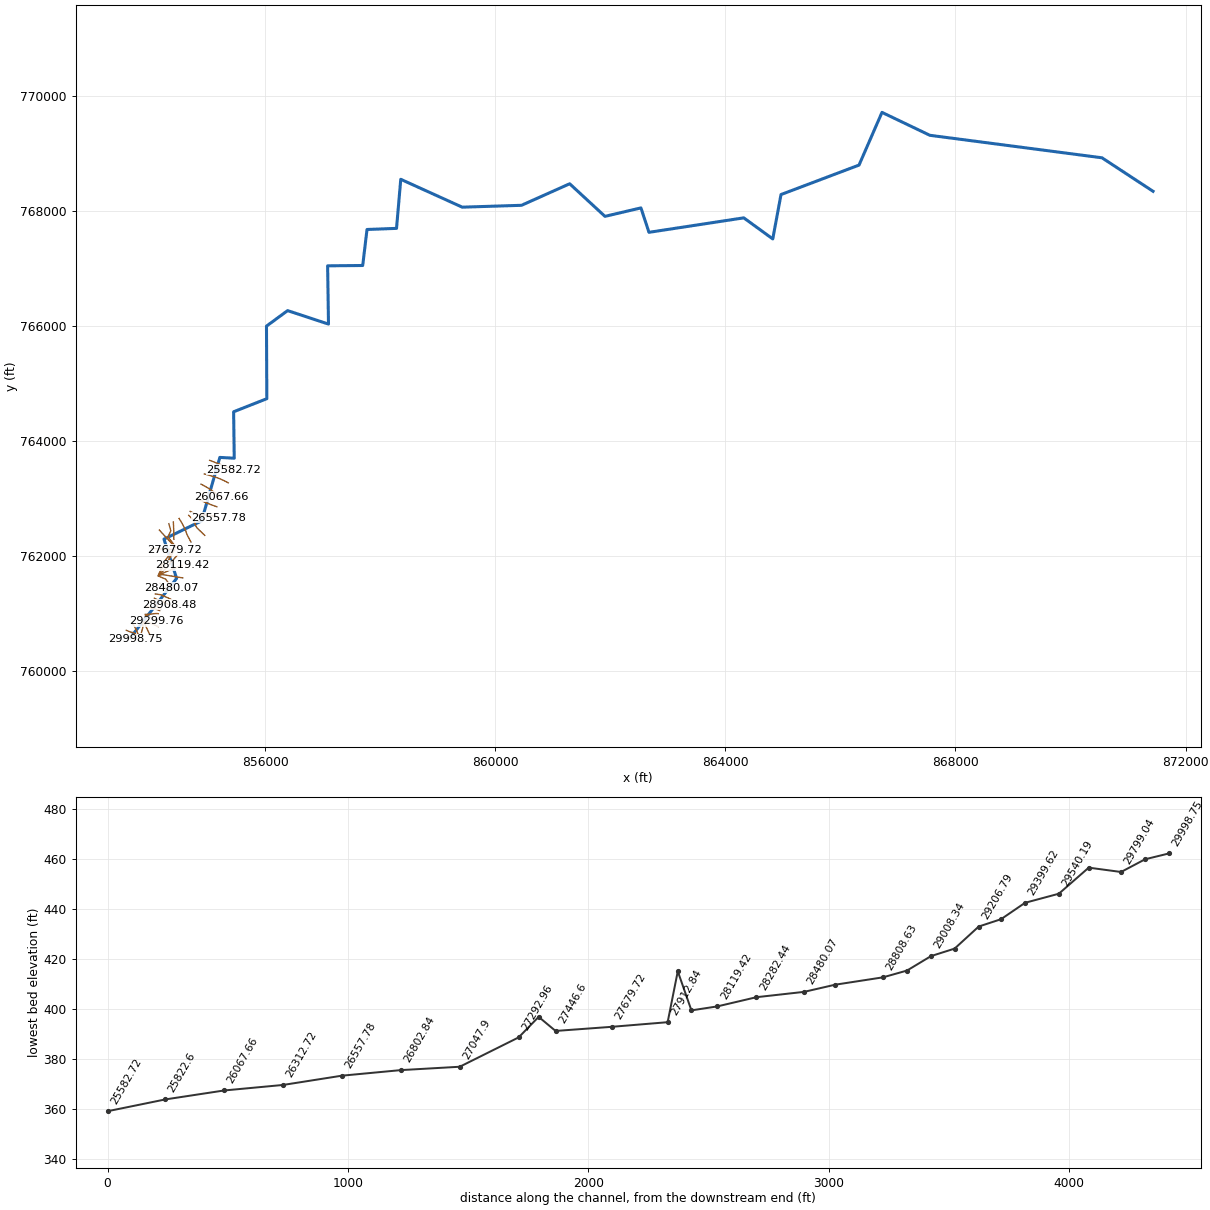
--- 9783_ras.prj (project) ---

Proj Title=9783
Current Plan=p01
Default Exp/Contr=0.3,0.1
English Units
Geom File=g01
Flow File=f01
Plan File=p01
Y Axis Title=Elevation
X Axis Title(PF)=Main Channel Distance
X Axis Title(XS)=Station
BEGIN DESCRIPTION:
RFD model 9783 exported to HEC-RAS
END DESCRIPTION:

--- 9783_ras.p01 (plan) ---

Plan Title=Plan 01
Program Version=4.10
Short Identifier=Plan 01
Geom File=g01
Flow File=f01
Subcritical Flow
Calc Critical at every XS
Secant Critical Depth

--- 9783_ras.f01 (steady flow) ---

Flow Title=Flow 01
Program Version=5.01
Number of Profiles= 6
Profile Names=10yr,25yr,50yr,100yr,100plus,500yr
River Rch & RM=9783,109,29998.75
  595.65  905.19 1182.82 1417.07 2068.92 2845.27
River Rch & RM=9783,109,29898.89
  597.68  908.28 1186.87 1421.93 2076.01 2853.64
River Rch & RM=9783,109,29664.47
   600.1  911.98 1191.72 1427.74  2084.5 2863.68
River Rch & RM=9783,109,29540.19
  614.25  933.53 1219.96  1461.6 2133.94 2921.95
River Rch & RM=9783,109,29299.76
  717.03 1090.95 1426.92  1710.5 2497.33 3347.94
River Rch & RM=9783,109,29206.79
  719.74  1095.1 1432.36 1717.03 2506.86 3358.93
River Rch & RM=9783,109,29106.54
  720.91 1096.88 1434.69 1719.83 2510.95 3363.64
River Rch & RM=9783,109,29008.34
  722.07 1098.66 1437.03 1722.63 2515.03 3368.35
River Rch & RM=9783,109,28908.48
  730.19 1111.06  1453.3 1742.17 2543.57 3401.22
River Rch & RM=9783,109,28808.63
  745.21    1134 1483.42 1778.33 2596.37 3461.94
River Rch & RM=9783,109, 28609.4
  745.98 1135.18 1484.96 1780.19 2599.07 3465.05
River Rch & RM=9783,109,28480.07
  764.39 1163.31 1521.88 1824.51 2663.78 3539.19
River Rch & RM=9783,109,28282.44
  772.04 1174.99 1537.22 1842.92 2690.66  3569.9
River Rch & RM=9783,109,28119.42
  773.19 1176.74 1539.52 1845.68 2694.69  3574.5
River Rch & RM=9783,109,28011.73
 1268.67 1934.22 2534.53 3040.59 4439.26 5492.79
River Rch & RM=9783,109,27679.72
 1274.16 1942.62 2545.58 3053.88 4458.67 5513.48
River Rch & RM=9783,109, 27446.6
 1280.25 1951.99 2557.93 3068.75 4480.38 5536.73
River Rch & RM=9783,109,27376.23
 1287.02 1962.39 2571.64 3085.26 4504.48 5562.51
River Rch & RM=9783,109, 27047.9
 1337.47 2039.93 2673.88 3208.43  4684.3 5754.41
River Rch & RM=9783,109,26802.84
 1370.21 2090.13 2739.96  3287.9 4800.33 5877.17
River Rch & RM=9783,109,26557.78
 1382.88 2109.61 2765.65 3318.83 4845.49 5924.99
River Rch & RM=9783,109,26312.72
 1385.55 2113.71 2771.05 3325.33 4854.98 5935.04
River Rch & RM=9783,109,26067.66
 1412.79 2155.58 2826.26 3391.83 4952.07 6037.65
River Rch & RM=9783,109, 25822.6
 1420.09 2166.79 2841.03 3409.63 4978.05 6065.06
River Rch & RM=9783,109,25582.72
 1429.03 2180.53 2859.15 3431.45 5009.91 6098.64
River Rch & RM=9783,109,25087.43
 1521.16 2322.24  3046.1  3656.7 5338.78  6443.9
River Rch & RM=9783,109,24842.37
  1525.4 2328.77 3054.71 3667.06 5353.91  6459.7
River Rch & RM=9783,109,24578.31
 1873.37 2865.11 3763.31 4521.85  6601.9 7747.12
River Rch & RM=9783,109,24222.67
 1884.59 2882.38 3786.11 4549.32 6642.01 7787.78
River Rch & RM=9783,109,23862.13
 2303.73  3528.9 4640.87  5580.7 8147.83  9295.5
River Rch & RM=9783,109,23604.31
 2305.79 3532.09 4645.09  5585.8 8155.27 9302.86
River Rch & RM=9783,109,23326.44
 2313.14 3543.46 4660.14 5603.99 8181.83 9329.16
River Rch & RM=9783,109,22950.93
 2385.19    3655 4807.97 5782.74  8442.8 9587.41
River Rch & RM=9783,109,22756.98
 2392.54 3666.35 4822.98 5800.86 8469.25  9613.4
River Rch & RM=9783,109,22636.84
 2395.42 3670.81 4828.91 5808.04 8479.73 9623.79
River Rch & RM=9783,109,22391.78
 2400.31 3678.41 4838.99 5820.24 8497.56 9641.43
River Rch & RM=9783,109,22146.72
 2409.91 3693.26 4858.68 5844.04 8532.29 9675.65
River Rch & RM=9783,109,21901.66
 2487.37 3813.21 5017.68 6036.31 8813.02 9951.83
River Rch & RM=9783,109, 21656.6
 2491.08 3818.96 5025.32 6045.57 8826.53 9965.15
River Rch & RM=9783,109,21411.54
 2498.48 3830.47  5040.6 6064.07 8853.55 9991.77
River Rch & RM=9783,109,21206.34
 2501.33 3834.89 5046.47 6071.19 8863.94   10002
River Rch & RM=9783,109,20921.43
 2511.28 3850.34    5067 6096.06 8900.2510037.78
River Rch & RM=9783,109,20676.37
 2514.09 3854.73 5072.83 6103.14 8910.5810047.99
River Rch & RM=9783,109,20431.31
 2540.02  3895.2 5126.77 6168.66 9006.2410142.77
River Rch & RM=9783,109,20186.25
 2544.82 3902.67 5136.69 6180.69  9023.810160.05
River Rch & RM=9783,109,19941.19
 2547.57 3906.98 5142.44 6187.69 9034.0310170.22
River Rch & RM=9783,109,19696.13
 2684.27 4120.73 5427.59 6534.45  9540.310670.47
River Rch & RM=9783,109,19451.07
 2692.16 4133.09 5444.09 6554.53 9569.6210699.37
River Rch & RM=9783,109,19158.85
 2696.41 4139.79 5453.07  6565.5 9585.6310715.31
River Rch & RM=9783,109,18967.45
 2783.74  4276.4 5635.35 6787.21 9909.3211033.04
River Rch & RM=9783,109,18829.23
 2785.85 4279.72 5639.81 6792.65 9917.2711040.91
River Rch & RM=9783,109,18690.77
 2786.64 4280.97 5641.48 6794.69 9920.2511043.86
River Rch & RM=9783,109,18562.96
 2787.69 4282.63 5643.71 6797.42 9924.23 11047.8
River Rch & RM=9783,109,18463.46
  2789.8 4285.95 5648.16 6802.86 9932.1811055.67
River Rch & RM=9783,109,18363.96
 2795.61  4295.1 5660.43 6817.84 9954.0511077.29
River Rch & RM=9783,109,18272.62
 2801.89 4305.03 5673.75 6834.13 9977.8311100.87
River Rch & RM=9783,109,18164.96
 2802.95 4306.69 5675.98 6836.85  9981.811104.79
River Rch & RM=9783,109,18065.46
    2804 4308.35  5678.2 6839.57 9985.7711108.72
River Rch & RM=9783,109,17926.27
 2805.32 4310.42 5680.99 6842.97 9990.7311113.63
River Rch & RM=9783,109,17726.72
 2818.99 4331.99  5709.9 6878.29 10042.311164.61
River Rch & RM=9783,109,17520.71
 2828.62  4347.2 5730.34  6903.310078.8211200.84
River Rch & RM=9783,109,17274.46
 2833.04  4354.2 5739.74  6914.8 10095.611217.46
River Rch & RM=9783,109,17028.21
 2835.85 4358.66 5745.75 6922.1810106.3811228.22
River Rch & RM=9783,109,16781.97
 2851.89 4384.17 5780.13 6964.3810167.9911289.73
River Rch & RM=9783,109,16535.72
 2855.45 4389.82 5787.76 6973.7410181.6711303.38
River Rch & RM=9783,109,16289.47
 2857.71 4393.43 5792.63 6979.7310190.4111312.15
River Rch & RM=9783,109,16043.22
 2861.47 4399.44 5800.75 6989.7210204.9911326.77
River Rch & RM=9783,109,15796.97
 2866.98 4408.24 5812.65 7004.3510226.3511348.19
River Rch & RM=9783,109,15550.73
 2895.98 4454.43 5874.99 7080.96 10338.211459.91
River Rch & RM=9783,109,15304.48
 2901.46 4463.19 5886.83 7095.5310359.4811481.23
River Rch & RM=9783,109,15058.23
 2904.21 4467.57 5892.77 7102.8310370.1311491.89
River Rch & RM=9783,109,14811.98
 2907.46 4472.76 5899.77 7111.4510382.7211504.48
River Rch & RM=9783,109,14565.73
  2910.7 4477.94 5906.77 7120.0610395.2911517.06
River Rch & RM=9783,109,14283.88
 2935.21 4517.15 5959.85 7185.4210490.7211612.71
River Rch & RM=9783,109,14013.36
 3174.36 4896.43  6470.4 7811.2411404.4112511.75
River Rch & RM=9783,109,13826.99
 3175.08 4897.58 6471.96 7813.1711407.2312514.56
River Rch & RM=9783,109, 13603.7
    3189 4919.93 6502.28 7850.5811461.8412568.85
River Rch & RM=9783,109,13334.49
 3191.39 4923.77 6507.49 7857.0211471.2412578.19
River Rch & RM=9783,109,13088.25
  3198.8 4935.68 6523.65 7876.9711500.3812607.16
River Rch & RM=9783,109,   12842
  3201.2 4939.53 6528.87 7883.4111509.78 12616.5
River Rch & RM=9783,109,12595.75
 3205.01 4945.65 6537.19 7893.6911524.7912631.43
River Rch & RM=9783,109,12366.88
 3217.74 4966.08 6564.88 7927.8411574.6512680.86
River Rch & RM=9783,109,12103.25
 3222.07 4973.01 6574.28 7939.4411591.5812697.63
River Rch & RM=9783,109,11784.99
 3239.77 5001.43 6612.83    798711661.0212766.47
River Rch & RM=9783,109,11610.76
 3246.39 5012.09 6627.32 8004.9111687.1712792.49
River Rch & RM=9783,109,10921.31
 3261.88 5036.97 6661.08 8046.5811748.0112852.79
River Rch & RM=9783,109,10040.08
 3453.28 5342.23 7073.51 8553.7312488.4413576.21
River Rch & RM=9783,109,9205.711
 3504.58 5424.79 7185.68 8692.3412690.8213775.22
River Rch & RM=9783,109,8363.058
 4606.16 7163.75 9520.77 11547.316859.0617677.98
River Rch & RM=9783,109,7784.993
  4613.6 7175.73 9537.0711567.4616888.4917705.78
River Rch & RM=9783,109,7509.764
  4617.3 7181.71  9545.211577.5216903.1817719.67
River Rch & RM=9783,109,7294.626
 4620.12 7186.26  9551.4 11585.216914.3917730.29
River Rch & RM=9783,109,6977.599
 4624.66  7193.6 9561.41 11597.616932.4917747.45
River Rch & RM=9783,109,6601.624
  4627.9 7198.84 9568.5511606.4416945.4117759.69
River Rch & RM=9783,109,6185.844
 4642.89 7223.02 9601.4911647.2117004.9317815.99
River Rch & RM=9783,109,5828.067
 4894.59 7628.6210153.3112329.6918001.3418752.22
River Rch & RM=9783,109,5572.604
 4896.28 7631.3610157.0612334.3418008.1318758.61
River Rch & RM=9783,109,5469.949
 4896.92 7632.3910158.4612336.0818010.6818761.01
River Rch & RM=9783,109,4810.305
 4903.07 7642.3510172.0512352.9318035.2818784.17
River Rch & RM=9783,109,4419.528
 4900.32 7637.8910165.9612345.3818024.2618773.79
Boundary for River Rch & Prof#=9783,109,1
Up Type= 0
Dn Type= 2
Boundary for River Rch & Prof#=9783,109,2
Up Type= 0
Dn Type= 2
Boundary for River Rch & Prof#=9783,109,2
Up Type= 0
Dn Type= 2
Boundary for River Rch & Prof#=9783,109,2
Up Type= 0
Dn Type= 2
Boundary for River Rch & Prof#=9783,109,2
Up Type= 0
Dn Type= 2
Boundary for River Rch & Prof#=9783,109,2
Up Type= 0
Dn Type= 2

--- 9783_ras.g01 (geometry) ---

Geom Title=9783
Program Version=4.10

River Reach=9783,109
Reach XY= 30
853652.870013773760581.850639405854459.222487556761614.829540443
854239.080188885 762297.05783756854893.150082798762615.039552159
855210.677156975763718.403544303855460.878235556763704.460899674
855450.184437608764511.968576707856027.582005901764739.514865587
856021.513193951766001.200233639856388.861188432766270.754569162
857099.616900882766036.372612071857084.530292962767049.662277666
857694.667529152767055.139054066857769.335079143  767681.4056929
858282.449486046767700.644735758858356.087250587768553.566007098
859424.825806753768069.371871385860455.442560337768101.740947219
861292.958069401768476.089129391861906.715058577767909.524835707
862531.914607155768056.570833598862671.460712986767631.963203397
864319.374323667767883.454703583864823.873099438767517.092844929
864967.030618479768288.539799186866323.605961037768801.005224473
 866722.86179088 769717.32227549867555.406111362769318.728232252
870547.429810794 768927.80640233871435.606428128768345.354027828

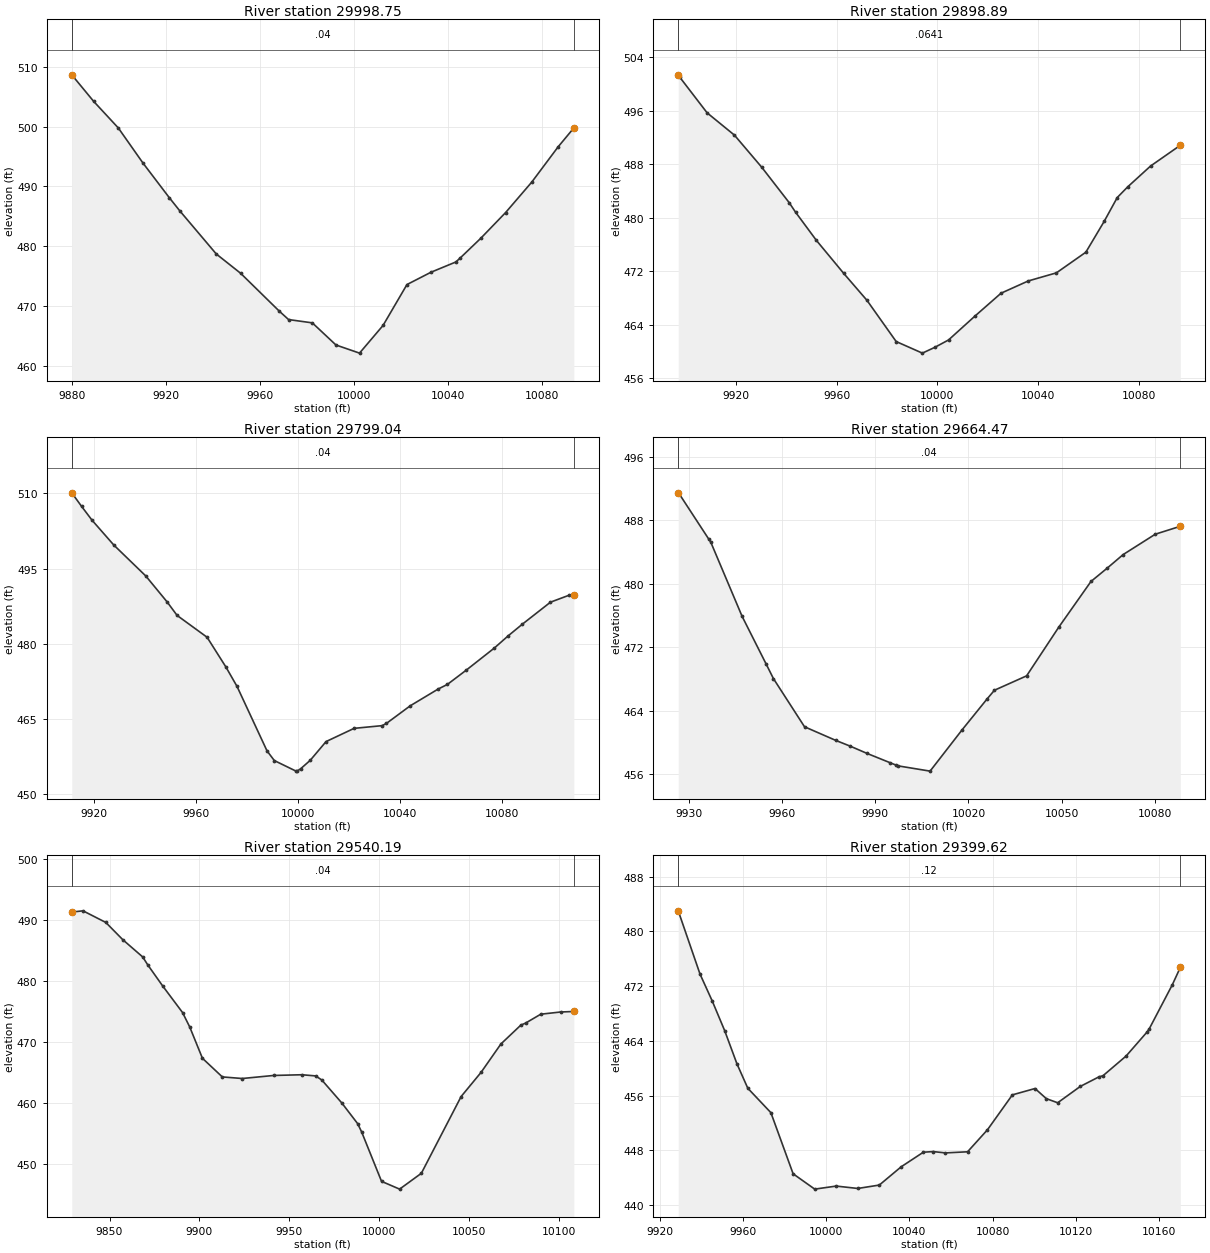
Type RM Length L Ch R = 1 ,29998.75,99.854600,99.854600,99.854600
XS GIS Cut Line= 6
853536.166469057760609.026894234853615.243663197760585.872415718
853664.341134879760583.247049899 853683.74789087760579.555133119
853716.596910556760568.103437793853740.939892938760555.632277763
#Sta/Elev= 23
9879.796508.70359889.089504.26999899.609499.80129910.129493.91119921.349488.1025
9925.824485.89319941.322478.68529951.652475.46449968.144469.10589972.098 467.697
9982.208467.14529992.269463.4371 10002.3462.074510012.31466.710810022.49473.5622
10032.72475.627310043.32477.348910045.24478.045310053.91481.3139 10064.5 485.632
10075.63490.732310086.86496.644510093.54499.8058
#Mann= 3 , 0 , 0
9879.796    0.04       09879.796    0.04       010093.54    0.04       0
#XS Ineff= 2 , 0
       0                               0
Bank Sta=9879.796,10093.54
Exp/Cntr=0.3,0.1

Type RM Length L Ch R = 1 ,29898.89,99.854500,99.854500,99.854500
XS GIS Cut Line= 6
853584.421478438760713.062096455853645.298120649760687.451440167
853708.226245711760669.261169614853723.535893844760662.126903336
853741.054833009760651.148120495853763.925148225 760631.33761794
#Sta/Elev= 24
9897.095501.33599897.723500.97119908.572495.6491 9919.42492.31689930.269487.5104
9941.118482.24249943.673480.80499951.967476.57899962.816 471.6469972.023467.6282
9983.637461.45929994.041459.7268    9999460.595710004.43461.693310014.85465.2427
10025.28468.685310036.12470.522210047.27471.728710058.96474.815510066.21479.4081
10071.43482.9914 10075.6484.592610084.66487.699410096.47490.8019
#Mann= 3 , 0 , 0
9897.095  0.0641       09897.095  0.0641       010096.47  0.0641       0
#XS Ineff= 2 , 0
       0                               0
Bank Sta=9897.095,10096.47
Exp/Cntr=0.3,0.1

Type RM Length L Ch R = 1 ,29799.04,134.563700,134.563700,134.563700
XS GIS Cut Line= 6
853690.157967291760828.086253458853712.827883254760798.374326633
853739.385199183760755.477720245853740.617530929760753.902487436
853742.483169394760750.661640602 853785.74581326760656.659599469
#Sta/Elev= 30
9911.175510.08259915.057507.36219919.158 504.6129927.636499.70359940.214493.5263
9948.548488.38299952.517485.66099964.278481.31569971.672475.38919976.039471.5164
9987.801458.68359990.669456.7554    9999454.69649999.607454.6487   10001455.1195
10004.74456.790210010.97460.533510021.98463.169510032.99463.707610034.68464.1571
   10044467.6578   10055471.0084 10058.6471.921310066.01474.769110077.02479.1668
10082.52481.626410088.03 483.92510099.04488.299410106.44 489.70210108.22489.7853
#Mann= 3 , 0 , 0
9911.175    0.04       09911.175    0.04       010108.22    0.04       0
#XS Ineff= 2 , 0
       0                               0
Bank Sta=9911.175,10108.22
Exp/Cntr=0.3,0.1

Type RM Length L Ch R = 1 ,29664.47,124.280500,124.280500,124.280500
XS GIS Cut Line= 6
853867.466523186760835.151503212853869.879306109760825.587636806
853872.427356188760807.304950162853873.287637199760780.218049665
 853872.84102479 760767.54917912853848.895088223760677.233772333
#Sta/Elev= 25
9926.621491.47769926.778 491.4439936.485485.61459937.078485.26859947.175475.8994
9954.944469.85999957.251468.05479967.256461.97869977.261460.26739982.045459.5196
9987.266458.63549994.722457.45569996.722457.14099997.307457.049810007.66 456.384
10018.01461.613510026.02465.494510028.37 466.58410038.72468.397410049.07474.5383
10059.43480.298410064.61481.966210069.78483.689310080.14486.263110088.18487.2582
#Mann= 3 , 0 , 0
9926.621    0.04       09926.621    0.04       010088.18    0.04       0
#XS Ineff= 2 , 0
       0                               0
Bank Sta=9926.621,10088.18
Exp/Cntr=0.3,0.1

Type RM Length L Ch R = 1 ,29540.19,140.574000,140.574000,140.574000
XS GIS Cut Line= 2
853886.889036875760860.646451445854006.512930943760608.372790286
#Sta/Elev= 30
9829.011491.3518 9835.26491.55789847.942489.65369857.395486.82489868.462483.9983
9871.282482.6948 9879.53479.26119890.597474.89859894.622472.51869901.664467.4028
9912.732464.34189923.799464.08399941.301464.58199957.001464.69989964.641464.5063
9968.068463.83669979.135460.0915 9987.98456.68949990.203455.330710001.27447.2328
10011.32445.9578 10023.4448.549110045.54461.134510056.61465.087910067.67469.7481
10078.74472.832510081.34473.158110089.81474.619210100.88474.981910108.21475.0632
#Mann= 3 , 0 , 0
9829.011    0.04       09829.011    0.04       010108.21    0.04       0
#XS Ineff= 2 , 0
       0                               0
Bank Sta=9829.011,10108.21
Exp/Cntr=0.3,0.1

Type RM Length L Ch R = 1 ,29399.62,99.854500,99.854500,99.854500
XS GIS Cut Line= 6
853916.766406666760870.269102473853929.618542021760860.129110514
853959.356775932760845.841886425854008.010086383760832.697032189
854054.008601634760816.196582373854138.407412183760777.963376829
#Sta/Elev= 30
9928.903483.00359939.391473.74559945.274469.80619951.244465.47569957.118460.6457
9962.339457.07349973.433453.50479984.125444.56719994.507442.328510004.85442.7744
 10015.2442.426710025.55442.923210036.09445.599910046.72447.724810051.46447.8154
10057.34447.624110067.97 447.78610077.54451.006910089.51 456.10710100.39457.0325
10105.82455.552510111.28 454.95110122.17457.342910131.09458.733610133.06458.9032
10144.15461.776810154.22465.286110155.29465.759110166.42 472.22110170.22474.7334
#Mann= 3 , 0 , 0
9928.903    0.12       09928.903    0.12       010170.22    0.12       0
#XS Ineff= 2 , 0
       0                               0
Bank Sta=9928.903,10170.22
Exp/Cntr=0.3,0.1

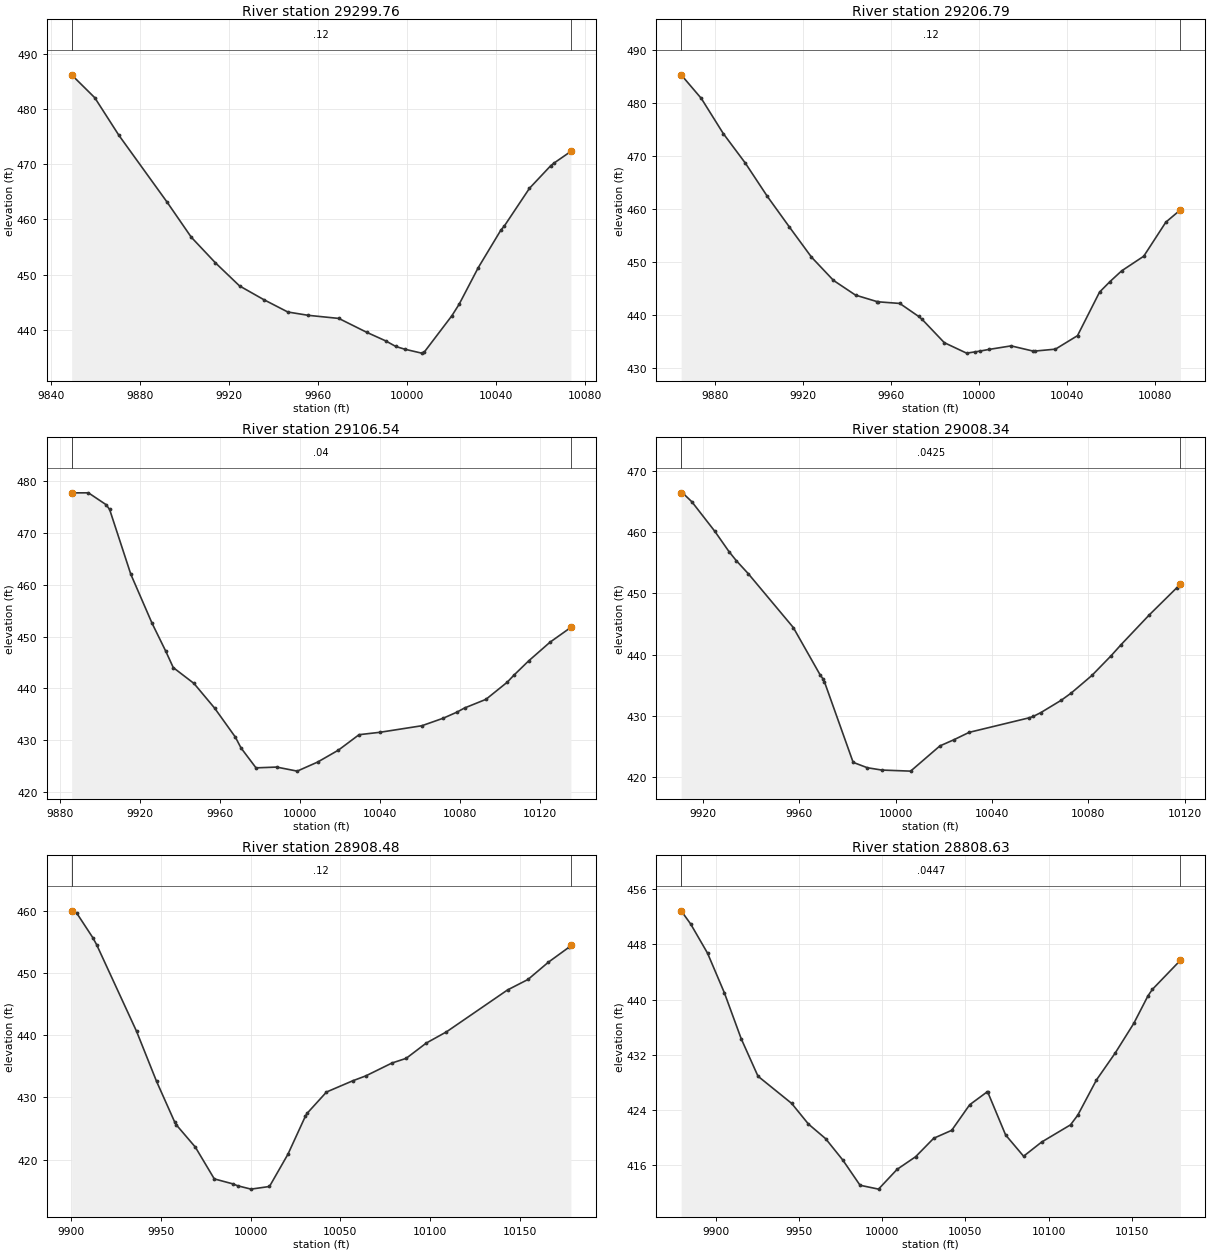
Type RM Length L Ch R = 1 ,29299.76,92.977600,92.977600,92.977600
XS GIS Cut Line= 6
853915.400205115760977.020058097854008.346069087760937.815860598
854028.907446482760925.721416227854062.519639238760898.294705437
854087.933270542760882.262655368854111.909208514760871.172857534
#Sta/Elev= 26
9849.134486.14279859.553 481.9979870.406475.19369892.112463.08579902.965456.7537
9913.818452.12129924.672  447.949935.525445.46979946.378443.22059955.563 442.619
9969.331442.05769981.859439.55019990.421437.99499994.982436.9779    9999436.4872
10006.57435.776810007.65435.897710020.22442.554210023.46444.621210032.04451.2292
 10042.2458.015510043.86458.821610055.12465.613410064.63469.678710066.14470.1701
10073.75472.2887
#Mann= 3 , 0 , 0
9849.134    0.12       09849.134    0.12       010073.75    0.12       0
#XS Ineff= 2 , 0
       0                               0
Bank Sta=9849.134,10073.75
Exp/Cntr=0.3,0.1

Type RM Length L Ch R = 1 ,29206.79,100.242500,100.242500,100.242500
XS GIS Cut Line= 6
853915.865803158760990.176124066854004.892694883760992.354935879
854049.016364306760998.632392235854075.891546795761002.561806834
854109.753256727761004.763527047854141.604319312 761002.17887885
#Sta/Elev= 30
9864.724485.27529873.861480.83179883.864474.19689893.867468.6337 9903.87462.3546
9913.873 456.5929923.876450.92799933.879446.53639943.882443.76579953.777442.5242
9953.886442.51169963.986442.19519972.556439.74239974.087439.21089984.188434.8047
9994.288 432.8339998.345433.079410000.35433.2174 10004.4 433.525 10014.5434.1997
10024.61 433.20810025.51433.229510034.63433.581110044.66436.124510054.68444.3368
10059.44446.3277 10064.7 448.33710074.74451.097810084.77457.5122 10091.4459.8392
#Mann= 3 , 0 , 0
9864.724    0.12       09864.724    0.12       0 10091.4    0.12       0
#XS Ineff= 2 , 0
       0                               0
Bank Sta=9864.724,10091.4
Exp/Cntr=0.3,0.1

Type RM Length L Ch R = 1 ,29106.54,98.204000,98.204000,98.204000
XS GIS Cut Line= 6
853927.091315945761130.786940534853975.094471186761113.703501882
854024.558901783761100.528390295854062.293898936761091.372496492
854095.427017531761081.068459015854164.768689051761054.860607437
#Sta/Elev= 29
9885.901477.78029894.296477.78879903.161475.4957 9904.91474.57179915.525462.0407
9926.139452.59029932.987447.19189936.754444.01979947.105440.95849957.453436.1841
9967.802430.59689970.669 428.4829978.151424.6438 9988.49424.79539998.764424.0119
10009.06425.776810019.37428.067510029.71431.052710040.19431.517910061.13432.7822
10071.81434.235310078.75435.4226 10082.5436.215110093.19437.880210103.88441.2041
10107.04442.495110114.57445.314810125.26448.926110135.71451.7917
#Mann= 3 , 0 , 0
9885.901    0.04       09885.901    0.04       010135.71    0.04       0
#XS Ineff= 2 , 0
       0                               0
Bank Sta=9885.901,10135.71
Exp/Cntr=0.3,0.1

Type RM Length L Ch R = 1 ,29008.34,99.854600,99.854600,99.854600
XS GIS Cut Line= 6
854044.369875654761227.870727965854061.764783613761213.045688886
854084.328484685 761186.57585453854122.771284398761128.995407879
854138.313942775761112.761091182854186.266276137761080.431698068
#Sta/Elev= 29
9910.924466.41779911.752466.3153 9915.35464.96449924.891460.14519930.767456.8385
 9933.78455.36849938.767453.23769957.492444.44239968.561436.7663  9969.8436.0737
9970.437435.57259982.339422.4487 9988.24421.57039994.241421.192410006.21421.0181
10018.36425.131410024.12 426.12710030.51427.343510055.49 429.72110057.18429.9514
10060.28430.568310068.77432.586210072.87433.748710081.47436.621510089.37439.8053
10093.61441.6553 10105.2446.461510116.78450.949710118.25451.6075
#Mann= 3 , 0 , 0
9910.924  0.0425       09910.924  0.0425       010118.25  0.0425       0
#XS Ineff= 2 , 0
       0                               0
Bank Sta=9910.924,10118.25
Exp/Cntr=0.3,0.1

Type RM Length L Ch R = 1 ,28908.48,99.854500,99.854500,99.854500
XS GIS Cut Line= 6
 854072.47165198 761270.16989714854124.907962339761244.567262725
854145.382537052761237.662445528854185.759792095 761228.33274396
854215.890750831761216.303985896854326.008604005761158.093984373
#Sta/Elev= 29
9900.139459.98269902.952459.62879911.922455.67769914.081454.53999936.337440.6175
9947.466432.58539957.505426.09439958.589425.54819969.142421.98589979.696416.8833
9989.937416.09239992.763415.774710000.17415.238510010.46415.662910020.76420.8488
10030.53426.982510031.49427.436510042.26430.850610056.84432.649310064.23433.4508
10078.75435.5109 10086.7436.264510097.94438.729610109.18440.526610143.21447.2617
10154.61448.943910166.01451.725510177.41454.111510178.56 454.436
#Mann= 3 , 0 , 0
9900.139    0.12       09900.139    0.12       010178.56    0.12       0
#XS Ineff= 2 , 0
       0                               0
Bank Sta=9900.139,10178.56
Exp/Cntr=0.3,0.1

Type RM Length L Ch R = 1 ,28808.63,199.225400,199.225400,199.225400
XS GIS Cut Line= 6
854089.346502466761344.903373244854167.765068383761333.268621321
854195.509471113761325.819846719854227.954347414761309.949649348
854311.096140745  761276.0236849854370.036793439 761246.20270367
#Sta/Elev= 30
9879.263452.84939884.979450.93839895.088446.72259905.198440.98749915.307434.3334
9925.416428.88879945.635424.95259955.745421.95199966.031419.84569976.386416.7392
 9986.74413.09059997.836412.5298   10009415.395710020.11417.2212   10031419.9002
 10041.8421.0477 10052.6424.754210062.96426.5943 10063.4 426.622 10074.2420.3779
   10085417.2951 10095.8419.344110113.19421.844810117.56423.251910128.77428.3431
10139.97432.223210151.18436.532410159.75440.541810162.39441.473110179.24445.6893
#Mann= 3 , 0 , 0
9879.263  0.0447       09879.263  0.0447       010179.24  0.0447       0
#XS Ineff= 2 , 0
       0                10047.73       0
Bank Sta=9879.263,10179.24
Exp/Cntr=0.3,0.1

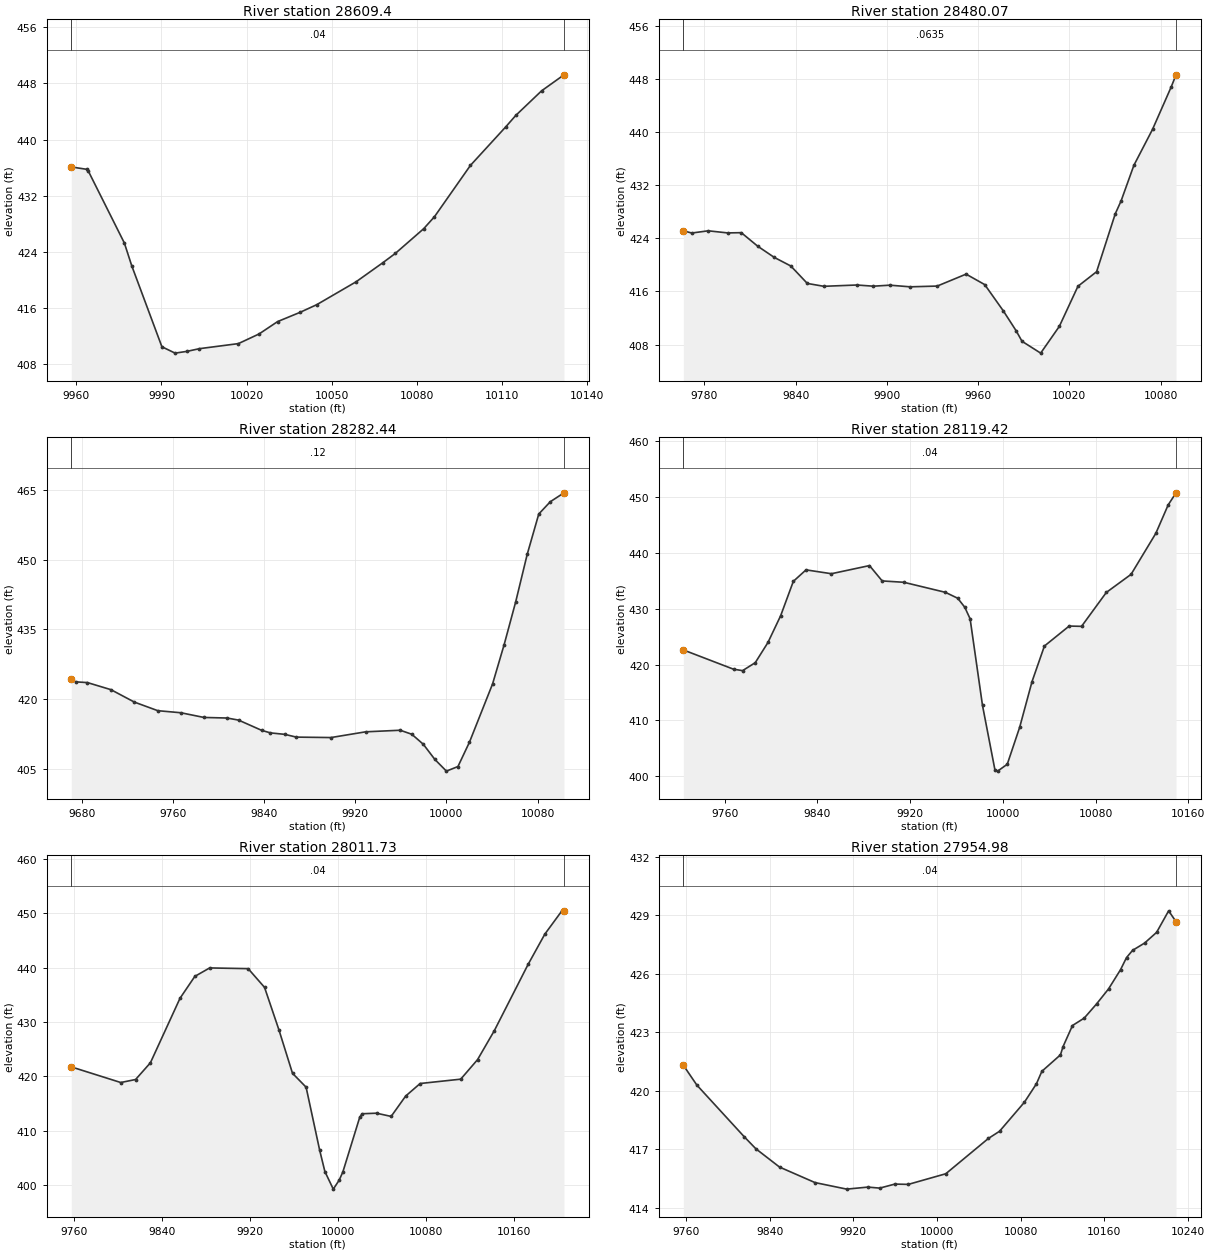
Type RM Length L Ch R = 1 , 28609.4,129.333300,129.333300,129.333300
XS GIS Cut Line= 6
854170.866228516761528.920075168854201.684467451761502.261531636
854203.202609412761500.959515984854207.303652921 761497.33048534
854266.227541094761441.224914321854301.303182848761414.769179843
#Sta/Elev= 24
9958.251436.10119963.717435.76469964.243435.51869976.939425.26769979.529422.0352
9990.162410.48299994.814409.5794    9999409.8317 10003.4410.2161 10017.1410.9349
10024.36412.305410030.91414.072710038.86415.397610044.72 416.48710058.53419.7366
10067.86422.426310072.34423.773710082.36427.304410086.14429.004610098.83436.3287
10111.35441.853510114.78443.438310123.88446.946310131.77449.2267
#Mann= 3 , 0 , 0
9958.251    0.04       09958.251    0.04       010131.77    0.04       0
#XS Ineff= 2 , 0
       0                               0
Bank Sta=9958.251,10131.77
Exp/Cntr=0.3,0.1

Type RM Length L Ch R = 1 ,28480.07,197.632200,197.632200,197.632200
XS GIS Cut Line= 3
 854139.91332987761656.354273766854270.330595851761601.149515659
854375.915111661761452.396569759
#Sta/Elev= 30
9766.154425.13469771.677424.79989782.536425.13279795.282424.81529804.254 424.853
9815.113 422.8059825.972421.12679836.831419.8349 9847.69 417.2099858.549 416.778
9880.267 416.9749891.126416.79639901.985416.94859915.315416.70079933.118 416.814
9952.104418.61189964.367 417.033 9976.63413.06749984.948 410.1139988.893408.5015
10001.16406.719310013.42410.742910025.68416.786210037.94418.975110050.21427.6897
10054.06429.640710062.47434.995610074.73440.4055   10087446.786510090.19448.6138
#Mann= 3 , 0 , 0
9766.154  0.0635       09766.154  0.0635       010090.19  0.0635       0
#XS Ineff= 2 , 0
       09926.586                       0
Bank Sta=9766.154,10090.19
Exp/Cntr=0.3,0.1

Type RM Length L Ch R = 1 ,28282.44,163.017700,163.017700,163.017700
XS GIS Cut Line= 3
854141.215413183761664.166773766854211.792290509761681.415554702
854566.841805607761623.607854068
#Sta/Elev= 30
9670.792424.30659674.688 423.7569684.982423.59879705.571422.08099726.159419.4118
9746.696417.56919766.959417.12619787.223416.11569807.486415.99499817.618415.5442
9837.881413.34559845.596412.80069858.144412.48979868.276411.89689898.671411.8011
9929.066413.03159959.461413.37189969.593412.51249979.725410.35969989.856407.1057
9999.988 404.59510010.12405.581610020.25410.828610040.51423.320710050.65431.7374
10060.78440.920810070.91451.141510081.04459.785510091.17462.424210103.17464.3325
#Mann= 3 , 0 , 0
9670.792    0.12       09670.792    0.12       010103.17    0.12       0
#XS Ineff= 2 , 0
       09819.501                       0
Bank Sta=9670.792,10103.17
Exp/Cntr=0.3,0.1

Type RM Length L Ch R = 1 ,28119.42,107.692900,107.692900,107.692900
XS GIS Cut Line= 3
854158.351429164761677.321390644854355.694020838 761765.58371146
854551.314149231761839.289310142
#Sta/Elev= 30
9724.284422.62919767.584419.17659775.386418.9197 9786.34420.34519797.295423.9655
9808.249 428.7569819.204434.92119830.159436.97699852.068436.28899884.932437.7459
9895.886434.99579914.542434.7536 9950.41432.95439961.096431.89199967.172430.2791
9971.782428.20319982.469412.67559993.155401.18529995.534400.911110003.84402.1444
10014.53408.755410025.21416.9513 10035.9423.327510057.27426.909510067.96426.8568
10089.33432.9312 10110.7436.175510132.08443.529710142.76 448.63410149.51450.7838
#Mann= 3 , 0 , 0
9724.284    0.04       09724.284    0.04       010149.51    0.04       0
#XS Ineff= 2 , 0
       0 9955.81                       0
Bank Sta=9724.284,10149.51
Exp/Cntr=0.3,0.1

Type RM Length L Ch R = 1 ,28011.73,56.745400,56.745400,56.745400
XS GIS Cut Line= 5
854161.606637508761687.087015659854295.128308386761807.782653943
854332.654463947761859.336330026854334.115304917761860.702323049
854466.344114006762014.152514234
#Sta/Elev= 30
9757.378421.75649802.392418.89039815.872419.44199829.352422.50819856.312434.3574
9869.792438.37229883.272439.92119918.303439.79049933.216436.35469946.292428.5659
9958.661420.5794 9971.03418.03339983.398406.45129988.124 402.5529995.767399.3216
10001.13400.969310004.49402.4814 10019.8412.4928   10022413.157310035.12413.2586
10048.41412.666910061.61416.400610074.81418.707410111.72 419.50510127.04423.0889
10142.36428.4289   10173440.555210188.31446.140910203.63450.354210205.69450.4032
#Mann= 3 , 0 , 0
9757.378    0.04       09757.378    0.04       010205.69    0.04       0
#XS Ineff= 2 , 0
       09947.024                       0
Bank Sta=9757.378,10205.69
Exp/Cntr=0.3,0.1

Type RM Length L Ch R = 1 ,27954.98,42.142100,42.142100,42.142100
XS GIS Cut Line= 4
854158.351429164 761693.59743233854220.851429164761812.087015644
854315.898572892761928.294377923854408.394723833762091.159403697
#Sta/Elev= 30
9757.365421.30729770.257420.2908 9815.48 417.6469826.786  417.029849.398416.0832
9883.316 415.2889913.676414.95219933.848415.05639945.266415.00449959.686415.2103
9972.605415.195510008.45415.740610049.17417.550410059.88417.920510083.67419.4096
10095.17420.355210100.38420.995710118.17421.841210120.63422.261810129.67423.3459
10140.88423.724510152.67424.449810164.17 425.22310175.67 426.21210181.38426.8307
10187.17427.201210198.67427.575410210.17428.124610221.67429.228810228.75428.6704
#Mann= 3 , 0 , 0
9757.365    0.04       09757.365    0.04       010228.75    0.04       0
#XS Ineff= 2 , 0
       09935.372                       0
Bank Sta=9757.365,10228.75
Exp/Cntr=0.3,0.1

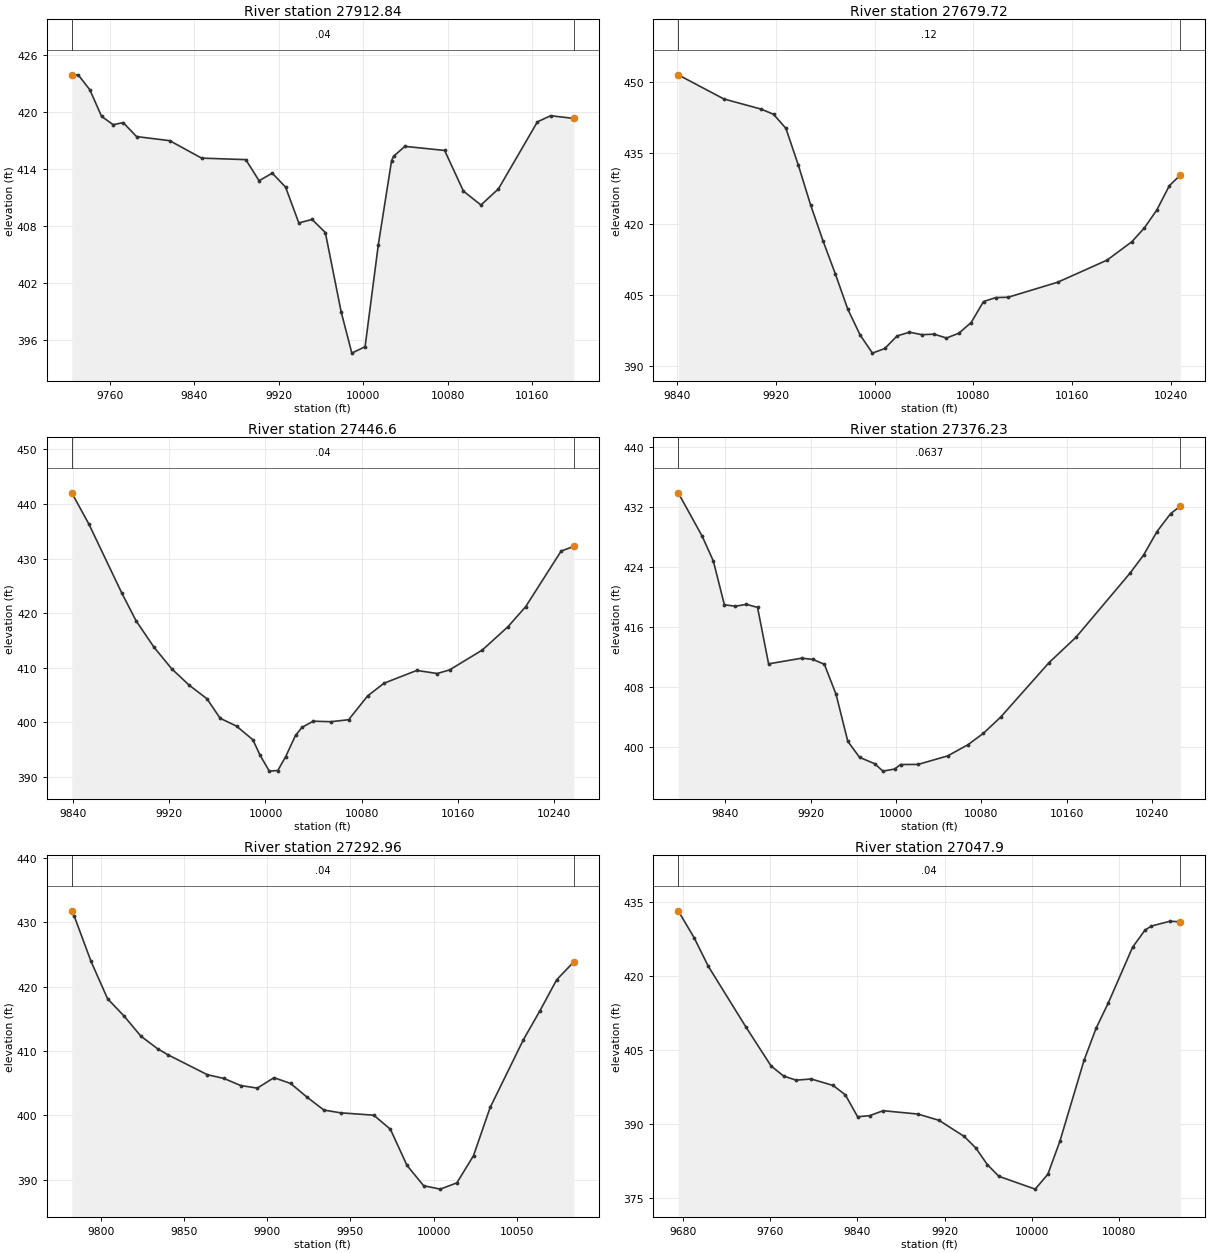
Type RM Length L Ch R = 1 ,27912.84,233.122800,233.122800,233.122800
XS GIS Cut Line= 4
854144.245526403761679.491529539854175.900635302761746.616146103
854185.537482619761828.581369475 854378.18639046762082.478848159
#Sta/Elev= 30
9723.915423.88719730.005423.89039741.062 422.3119752.118419.52179763.174418.6386
9772.573418.86299785.286417.3915 9816.64416.96149846.846415.12269888.716414.9645
9901.269412.74519913.822413.54289926.375412.06959938.927408.3037 9951.48408.6656
9964.033407.29259979.032398.93649989.139394.597510001.69395.278810014.24406.0287
 10026.8414.872210028.66415.311410039.35416.362210077.01415.930910094.84411.6451
10111.38410.191110127.93411.882610164.88418.942110177.43419.587510199.37419.2975
#Mann= 3 , 0 , 0
9723.915    0.04       09723.915    0.04       010199.37    0.04       0
#XS Ineff= 2 , 0
       0 9928.09                       0
Bank Sta=9723.915,10199.37
Exp/Cntr=0.3,0.1

Type RM Length L Ch R = 1 ,27679.72,233.122800,233.122800,233.122800
XS GIS Cut Line= 6
854018.330649302762141.325983882854082.931008663762132.880554489
854160.116745082 762126.73088598854346.884723932762120.124012847
854402.552070195762113.862792027854423.720616569762109.547788226
#Sta/Elev= 30
9840.812451.49979877.793446.40879908.037444.26039918.069443.16959928.101440.2071
9938.132 432.4819948.164424.01889958.196416.45239968.227409.45269978.259402.0422
9988.277396.58249998.281392.744510008.29393.721810018.29396.3777 10028.3397.1658
10038.31396.642510048.31396.745510058.32395.935910068.33396.944810078.33399.2061
10088.34403.639710098.35404.473210108.35404.546110148.38407.705810188.51412.3745
10208.63416.2717 10218.7419.1584 10228.8422.9421   10239428.0869 10247.9430.3401
#Mann= 3 , 0 , 0
9840.812    0.12       09840.812    0.12       0 10247.9    0.12       0
#XS Ineff= 2 , 0
       0                               0
Bank Sta=9840.812,10247.9
Exp/Cntr=0.3,0.1

Type RM Length L Ch R = 1 , 27446.6,70.365600,70.365600,70.365600
XS GIS Cut Line= 2
854158.662428093762455.504832903854442.176748542762149.197759671
#Sta/Elev= 30
9838.981442.02129853.295436.26689880.547423.69079892.476418.59399907.197413.8179
9921.919409.8565 9936.64 406.8149951.362404.34289962.304400.7738 9975.93399.3361
9989.556 396.8359995.527394.005610003.18391.098410010.25391.211710016.81 393.753
10024.97397.623510030.43399.117710039.69400.232210054.41400.142610069.13400.5041
10084.94404.864710098.57407.185310125.82409.528210142.74408.959510153.07409.6204
10180.32413.262510201.63417.532710216.35421.202310245.79431.363710256.36432.2225
#Mann= 3 , 0 , 0
9838.981    0.04       09838.981    0.04       010256.36    0.04       0
#XS Ineff= 2 , 0
       0                10035.79       0
Bank Sta=9838.981,10256.36
Exp/Cntr=0.3,0.1

Type RM Length L Ch R = 1 ,27376.23,83.272100,83.272100,83.272100
XS GIS Cut Line= 5
854324.190881223 762566.75505121854358.082742647762442.673940983
854310.215819887762337.531802692854321.807055672 762320.49144283
854448.428125054762157.833757436
#Sta/Elev= 30
9795.739433.93769818.291428.10929828.657424.82619839.024418.9684 9849.39418.7765
9859.756419.02729870.123418.61669880.489411.06889911.588 411.8289921.954411.6619
9932.797411.01749943.785406.98259954.772400.7116 9965.76398.57539980.075397.7081
9987.735396.72599998.723397.007810004.21397.6089 10020.7397.6254 10048.4398.7583
10067.46400.258710081.98401.787810098.26403.9667 10143.5411.235510168.84414.6328
10219.53423.2082 10232.2425.620610244.77428.762210257.55431.159610266.63432.1496
#Mann= 3 , 0 , 0
9795.739  0.0637       09795.739  0.0637       010266.63  0.0637       0
#XS Ineff= 2 , 0
       0                10036.34       0
Bank Sta=9795.739,10266.63
Exp/Cntr=0.3,0.1

Type RM Length L Ch R = 1 ,27292.96,245.058900,245.058900,245.058900
XS GIS Cut Line= 4
854402.496632949762596.528329985854409.255407864762440.372705889
854409.957881301762320.945401226854411.690209905762294.702532246
#Sta/Elev= 30
 9782.38431.8064 9783.91430.96279793.919423.97149803.929418.12749813.938415.4104
9823.947412.31549833.957410.36099840.272409.40549863.985406.31079873.994405.7234
9884.004404.62729894.013404.23079904.022405.84969914.032404.95229924.041402.7918
 9934.05400.81379944.055400.38679964.055400.01399974.055397.82989984.055392.1981
9994.056389.042810004.06388.513410014.06389.492410024.06393.724910034.06401.2123
10054.06411.759410064.07416.286210074.09421.089610084.11423.786710084.41423.7935
#Mann= 3 , 0 , 0
 9782.38    0.04       0 9782.38    0.04       010084.41    0.04       0
#XS Ineff= 2 , 0
       0                               0
Bank Sta=9782.38,10084.41
Exp/Cntr=0.3,0.1

Type RM Length L Ch R = 1 , 27047.9,245.058800,245.058800,245.058800
XS GIS Cut Line= 6
854501.803850667762657.087277856854547.541117126   762584.538577
854594.198414533762495.846177196854611.299138759762457.552728573
854637.946361064762380.733742478854708.543517762762247.017709901
#Sta/Elev= 30
9675.551433.28129690.162427.80799703.118422.02669737.389409.78949760.797401.7693
9772.224 399.7459783.638398.90699797.556399.14389817.718397.82679828.918395.9149
9840.118391.47899851.317391.70819863.535392.70559895.352392.0303  9914.8390.7556
9937.963387.47539948.548 385.1429959.133381.77179969.717379.389910003.06376.7861
10014.69379.819810025.77386.561410047.89402.959610058.96409.470110070.02414.5442
10092.41425.896910103.76429.365110109.64430.190810126.75431.172510136.18431.0435
#Mann= 3 , 0 , 0
9675.551    0.04       09675.551    0.04       010136.18    0.04       0
#XS Ineff= 2 , 0
       0                               0
Bank Sta=9675.551,10136.18
Exp/Cntr=0.3,0.1

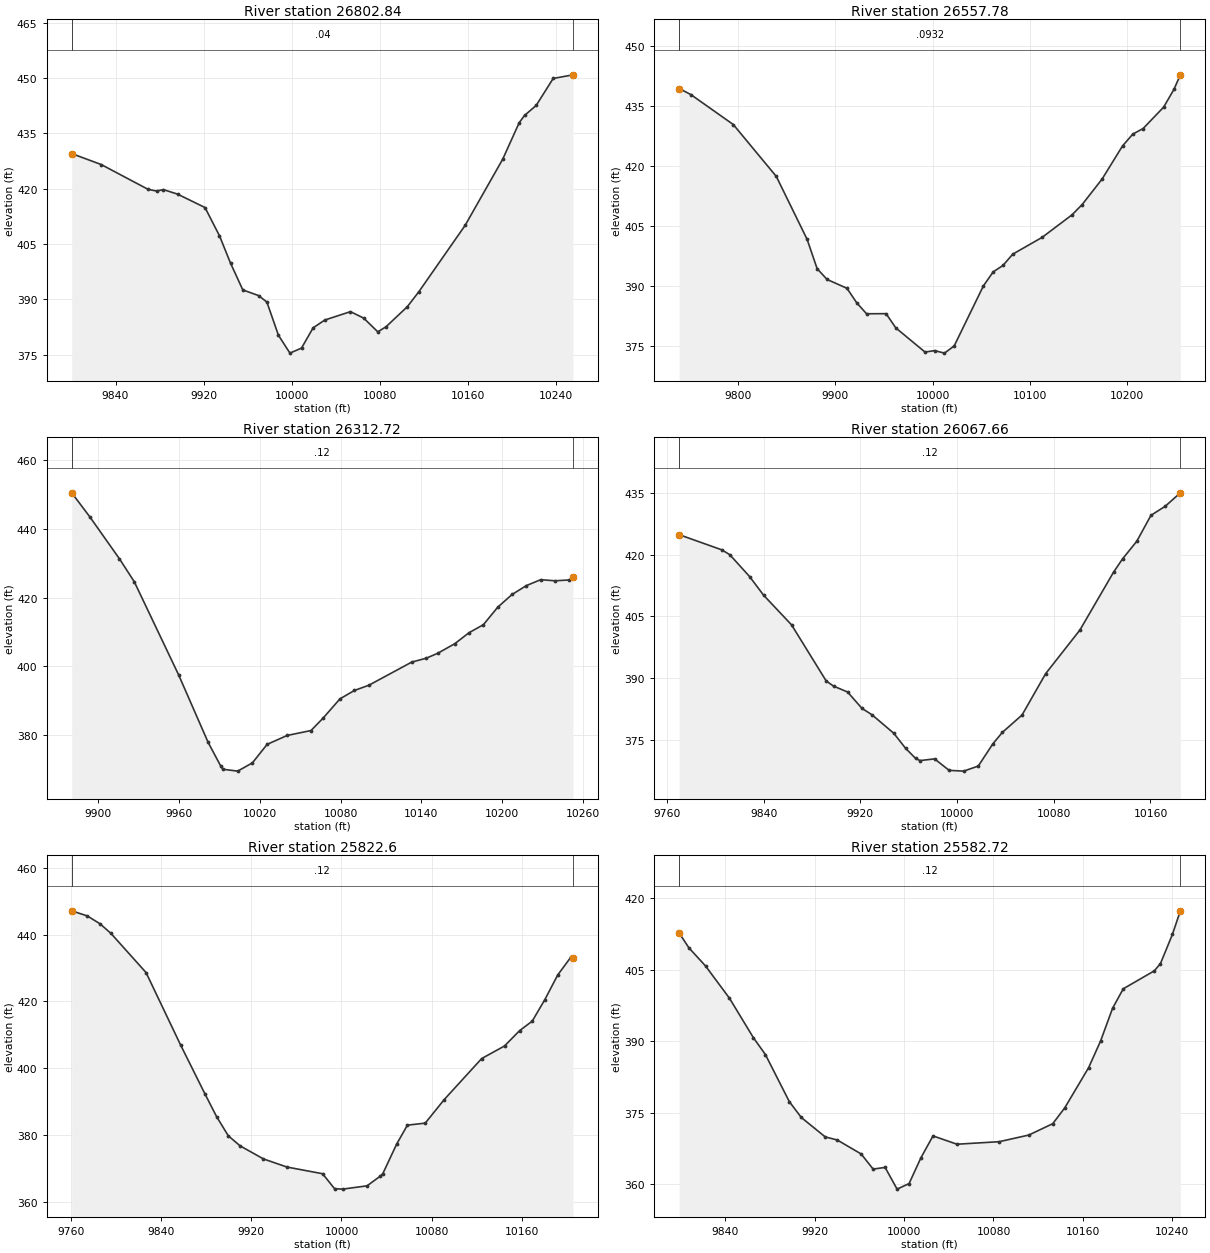
Type RM Length L Ch R = 1 ,26802.84,245.058900,245.058900,245.058900
XS GIS Cut Line= 6
854669.171066487762712.328519198854747.674783248762631.951448466
 854775.75208851 762580.56016348854792.912021562762526.118944523
854815.925288134762489.594800215854948.422342399762363.332881641
#Sta/Elev= 30
9800.242 429.5369826.998426.57249869.418419.86459877.232419.3776 9883.43419.7758
9896.258418.55329921.199414.91479934.313 407.2689944.365399.83879955.491392.5831
 9969.84391.03879977.368 389.2819987.822380.29969998.276375.439410008.78376.8098
 10019.3382.287410029.91384.412910053.23386.686110065.23384.929710078.04 381.207
10085.58382.613910104.77388.013110115.31392.098810157.24410.060210191.43428.0483
10206.34437.916210211.23439.889910221.75442.594410237.17449.902610255.15450.8948
#Mann= 3 , 0 , 0
9800.242    0.04       09800.242    0.04       010255.15    0.04       0
#XS Ineff= 2 , 0
       0                10050.32       0
Bank Sta=9800.242,10255.15
Exp/Cntr=0.3,0.1

Type RM Length L Ch R = 1 ,26557.78,245.058900,245.058900,245.058900
XS GIS Cut Line= 6
854694.447158028762779.939236238854790.561079048762735.547260151
854846.666358245762720.155862446855043.293700193762711.609069035
855118.330952262762694.676330284855191.299580113762669.851300008
#Sta/Elev= 30
 9739.31439.29489751.274437.79889795.034430.29729839.257417.34139870.943401.6249
 9881.24394.30499891.518391.60569911.897389.40779921.962385.78639932.027383.0458
9952.144383.06829962.148379.51329992.157 373.48710002.16373.838910012.17373.2144
10022.17375.008310052.22390.007510062.26393.499410072.31395.100410082.35397.9227
10112.63402.126210143.28407.7354 10153.6410.268410174.24416.675910195.29424.9568
10205.85427.913310216.41429.291810237.54 434.638 10248.1439.052110254.75442.7124
#Mann= 3 , 0 , 0
 9739.31  0.0932       0 9739.31  0.0932       010254.75  0.0932       0
#XS Ineff= 2 , 0
       0                               0
Bank Sta=9739.31,10254.75
Exp/Cntr=0.3,0.1

Type RM Length L Ch R = 1 ,26312.72,245.058900,245.058900,245.058900
XS GIS Cut Line= 6
854812.692133666763000.928449752854920.808365648762951.724492652
854922.648164499762950.940183957854963.406119716762932.885360044
855010.793376033762914.097322294855157.517486538762860.480709569
#Sta/Elev= 30
9880.214450.57189893.736443.5328 9915.71  431.349926.697424.68029959.658  397.55
9981.632377.85869991.092370.88389992.618370.048210003.57 369.50510014.51371.9159
10025.45377.303410040.36379.897210058.05381.328710066.97384.914310079.56390.5518
10090.32393.003510101.03394.517510132.97401.275410143.62402.381810152.19403.8212
10164.91406.621210175.56409.835110186.21412.165710196.85417.2548 10207.5420.9573
10218.15423.552110228.79425.270610239.44424.947610250.09425.195210252.77426.0498
#Mann= 3 , 0 , 0
9880.214    0.12       09880.214    0.12       010252.77    0.12       0
#XS Ineff= 2 , 0
       0                10037.21       0
Bank Sta=9880.214,10252.77
Exp/Cntr=0.3,0.1

Type RM Length L Ch R = 1 ,26067.66,245.058800,245.058800,245.058800
XS GIS Cut Line= 6
854883.288972897763253.774769029854924.250930837763233.273916038
855007.305146817763184.740466144855079.617157804763136.609871393
855153.237688015763086.882749442855235.673863883763035.986605781
#Sta/Elev= 30
9770.134424.92919805.595421.21399812.083420.03779828.389414.73089839.972 410.188
9863.136402.9483  9891.8389.27069897.883 388.0129909.465386.58789921.378382.5912
9929.714 381.0269947.762376.50749957.416372.8743 9965.81370.37789969.428369.8691
9981.441370.28459993.454367.487310005.52367.298110017.58368.534910029.64373.9488
10037.58376.767910053.77380.970410073.33391.066610101.67401.6977 10129.5415.8028
10136.92419.032510148.67423.318810160.43429.645110172.18 431.84410184.72435.1258
#Mann= 3 , 0 , 0
9770.134    0.12       09770.134    0.12       010184.72    0.12       0
#XS Ineff= 2 , 0
       0                               0
Bank Sta=9770.134,10184.72
Exp/Cntr=0.3,0.1

Type RM Length L Ch R = 1 , 25822.6,239.885600,239.885600,239.885600
XS GIS Cut Line= 6
854941.708810953763432.021042434855138.289201124763374.687309655
855171.741113434763362.829485057855268.606413028763322.468857855
855338.424336098  763287.0932193855356.696946289763276.539722596
#Sta/Elev= 30
9760.738 447.1989774.583445.66269785.814 443.3139795.416440.46429826.666428.6794
9857.245406.98839878.749 392.3869889.166385.49559899.582379.72559909.999376.7085
9930.832372.76719951.665370.33759983.232368.32949993.839363.8479   10001 363.712
 10022.7364.699710034.49367.626310036.69368.380610049.01377.261510058.47382.9035
10074.28383.509810091.14390.583910124.33 402.879 10144.6406.655510157.96411.2448
10169.17414.103410180.38420.569610191.82427.968910203.36433.250110205.32433.0461
#Mann= 3 , 0 , 0
9760.738    0.12       09760.738    0.12       010205.32    0.12       0
#XS Ineff= 2 , 0
       0                               0
Bank Sta=9760.738,10205.32
Exp/Cntr=0.3,0.1

Type RM Length L Ch R = 1 ,25582.72,495.291100,495.291100,495.291100
XS GIS Cut Line= 2
855032.930709813 763668.16073256855451.616522847 763506.59642884
#Sta/Elev= 30
9798.548412.74399807.327409.61179822.203405.8103 9843.64399.03939865.078390.7581
9875.797387.23269897.234377.34679907.953374.0284 9929.39369.95229940.109369.3114
9961.546 366.3739972.265 363.2029982.984 363.5559993.702359.000610004.42360.1617
10015.14365.619910025.86370.1636 10047.3368.4216 10085.1368.949310111.61370.3424
10133.05372.724810143.76376.0266 10165.2384.484510175.92390.080210186.64396.9373
 10196.2401.021610223.98404.785710229.51406.310610240.23 412.44110247.32417.3754
#Mann= 3 , 0 , 0
9798.548    0.12       09798.548    0.12       010247.32    0.12       0
#XS Ineff= 2 , 0
       0                               0
Bank Sta=9798.548,10247.32
Exp/Cntr=0.3,0.1