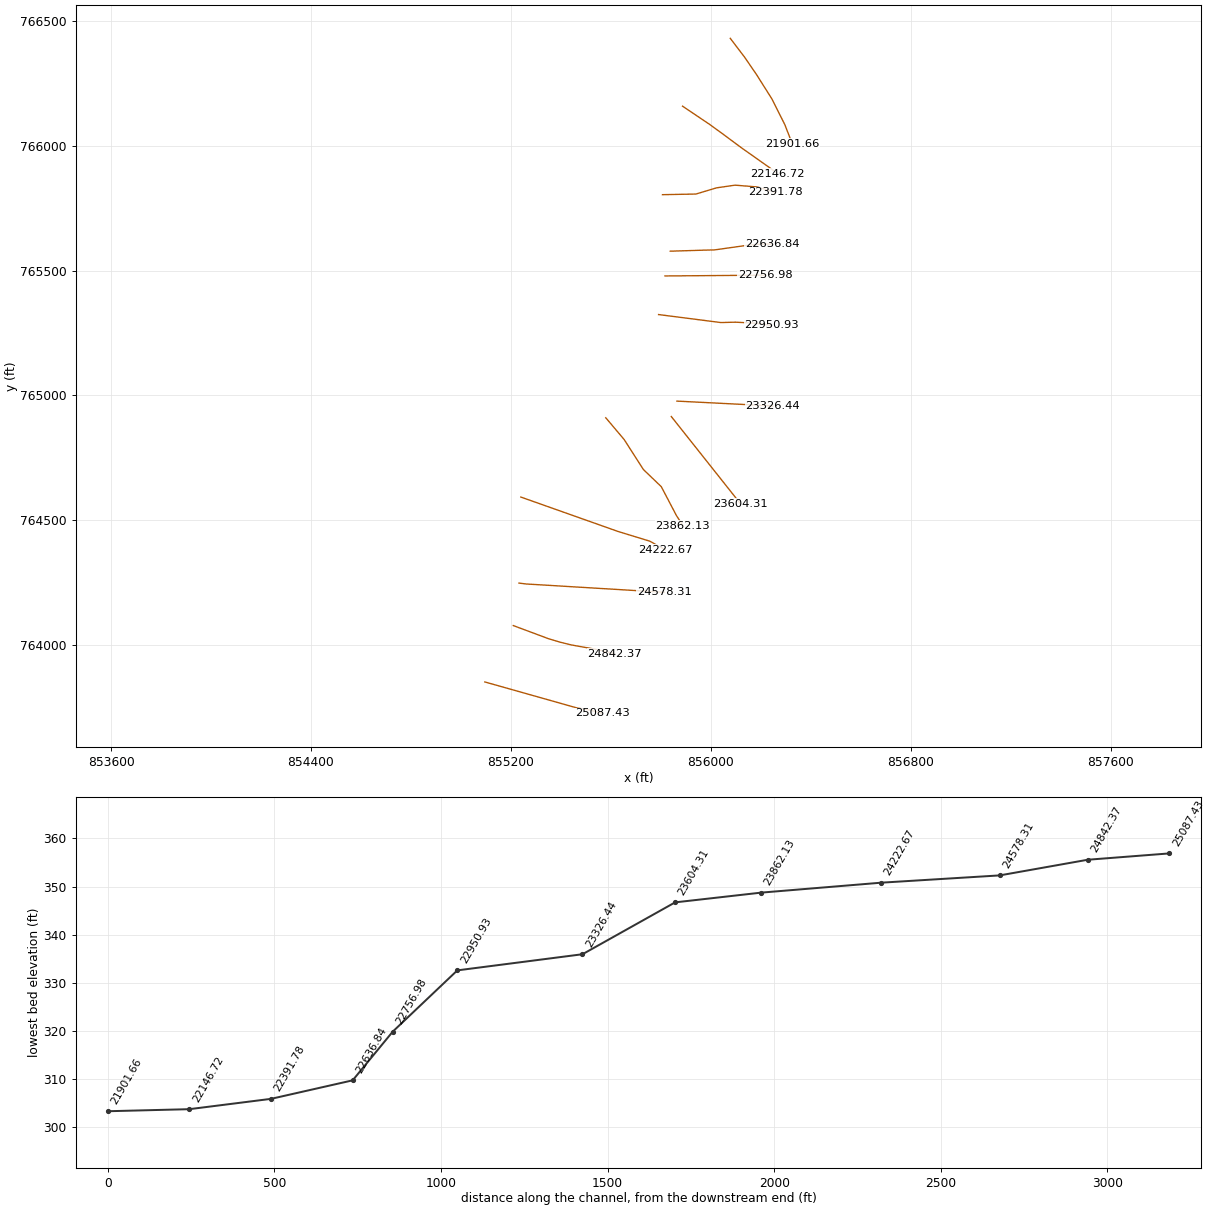
HEC-RAS study 9783_ras.prj: 9783

--- 9783_ras.g01 (geometry) --- (continued)

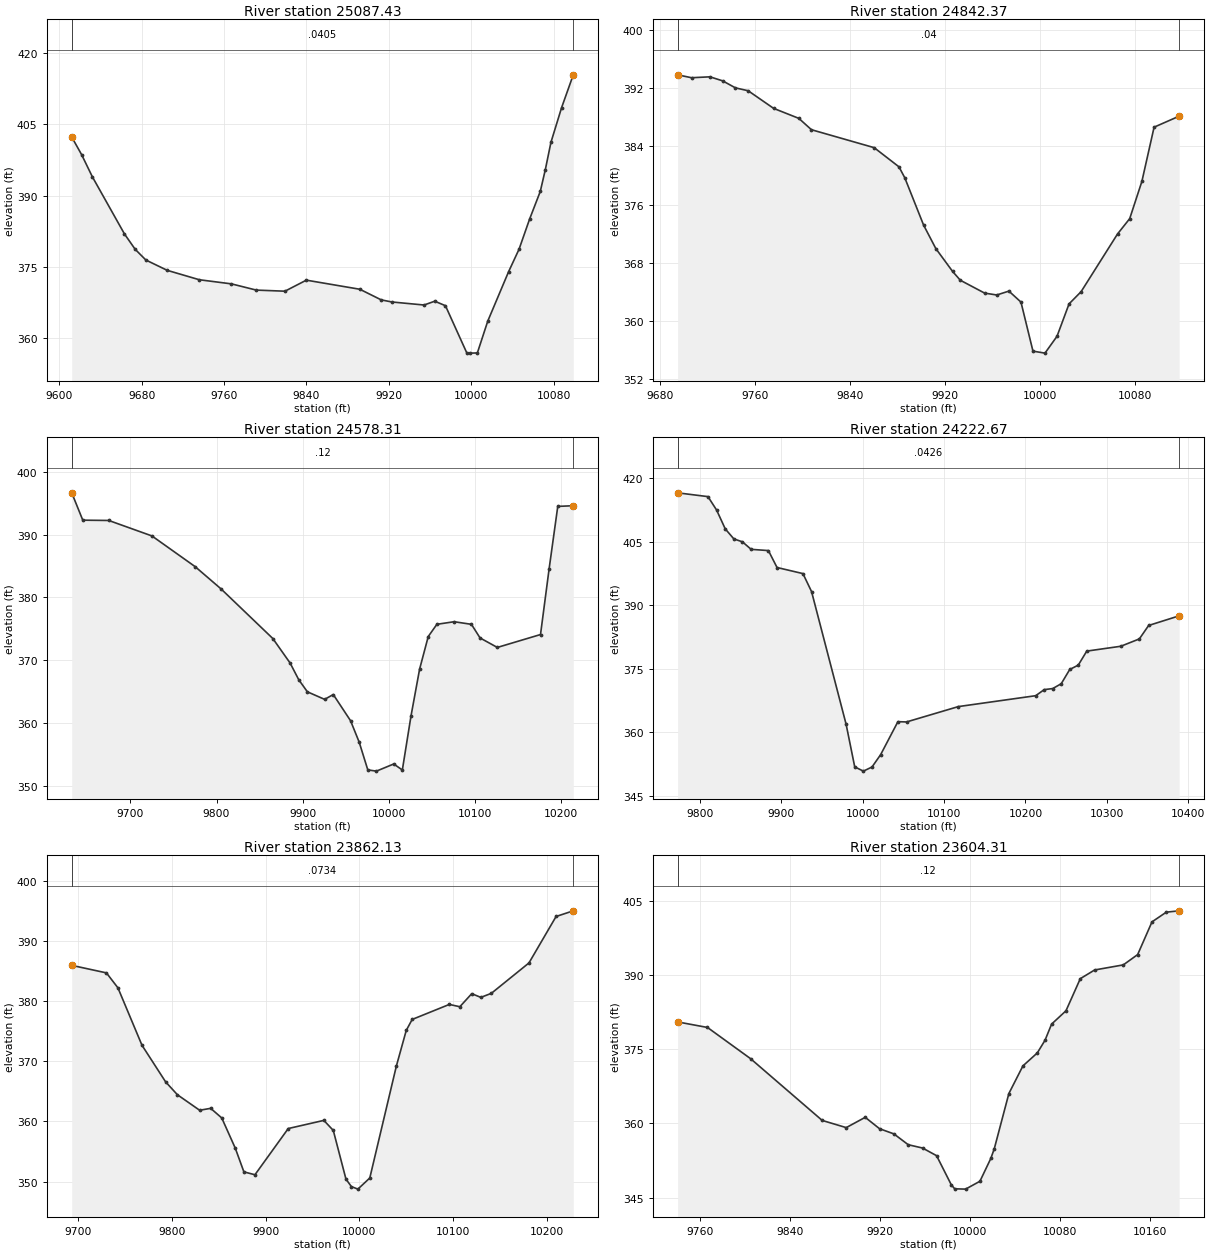
Type RM Length L Ch R = 1 ,25087.43,245.058800,245.058800,245.058800
XS GIS Cut Line= 5
855095.747905146763853.674560712855468.087158357763748.602017097
855470.074997262763748.381797796855518.957043386763740.623116913
855565.906429366 763727.91581388
#Sta/Elev= 30
9612.119402.35979621.733398.64029632.123393.99699663.295 381.9779673.685378.7477
9684.076376.48769704.857374.31259736.029372.3336  9767.2371.46659791.341370.1569
9819.153369.92629839.934372.24939891.887 370.3339912.668368.09689923.058 367.656
 9954.23367.01919964.621367.81959975.011366.87179995.792356.9154    9999356.8967
10005.99356.934910016.11363.636310036.36374.042810046.49378.762110056.75385.1108
10067.11 390.92210072.02395.524510077.47401.263410087.83408.561910099.13 415.445
#Mann= 3 , 0 , 0
9612.119  0.0405       09612.119  0.0405       010099.13  0.0405       0
#XS Ineff= 2 , 0
       0 9859.22                       0
Bank Sta=9612.119,10099.13
Exp/Cntr=0.3,0.1

Type RM Length L Ch R = 1 ,24842.37,264.058800,264.058800,264.058800
XS GIS Cut Line= 6
855209.602238942764079.250194202855350.088213728764026.813094087
855396.832854338764012.872751189855441.271977988764001.885164055
855545.463049808763983.229520841855615.548278701763967.038840405
#Sta/Elev= 30
 9695.15393.83929706.909393.4405 9722.39393.56429733.115393.0087 9743.84392.0472
9754.565391.64979775.999389.22859797.237387.85379807.856386.29349860.678383.8256
9881.548 381.1939886.452379.68819902.309373.1785 9912.61369.95119926.696366.8175
9933.212365.59979953.697363.83189963.913363.57269974.129364.10669984.297362.5955
9994.398 355.85310004.51355.579910014.65357.8939 10024.8362.352710034.94364.0277
10065.61  371.9610075.87374.070710086.13379.1911 10096.4386.642810117.49388.1534
#Mann= 3 , 0 , 0
 9695.15    0.04       0 9695.15    0.04       010117.49    0.04       0
#XS Ineff= 2 , 0
       0                               0
Bank Sta=9695.15,10117.49
Exp/Cntr=0.3,0.1

Type RM Length L Ch R = 1 ,24578.31,355.640400,355.640400,355.640400
XS GIS Cut Line= 4
 855232.28646443764249.232393527855261.702304384764245.585468508
855343.403623417764240.769105533855812.943546974 764212.40566598
#Sta/Elev= 30
9632.028396.64529644.839392.2908 9674.99392.24369725.077  389.789775.166384.8956
9805.221381.3505 9865.33373.44399885.367369.54489895.385  366.899905.403364.9624
 9925.44363.75559935.458364.52789955.494360.36059965.513356.95019975.531352.5234
9985.549352.330410005.59353.4673 10015.6  352.5110025.62361.094810035.64368.5836
10045.66373.765310055.68  375.7110075.71376.120710095.75 375.70610105.77373.5371
 10125.8372.0259 10175.9374.080110185.91384.562610195.93394.485210213.91394.5916
#Mann= 3 , 0 , 0
9632.028    0.12       09632.028    0.12       010213.91    0.12       0
#XS Ineff= 2 , 0
       0                               0
Bank Sta=9632.028,10213.91
Exp/Cntr=0.3,0.1

Type RM Length L Ch R = 1 ,24222.67,360.536300,360.536300,360.536300
XS GIS Cut Line= 4
855239.843318649764593.495158041855628.566807176764455.846198197
855755.966104226764416.922071545855817.749364511764382.642743864
#Sta/Elev= 30
9772.646416.57339809.942415.6752 9820.55412.51029831.159408.06239841.767405.6855
9852.375 404.9859862.984  403.229884.201 402.9289894.809398.92989926.634397.4911
9937.243393.23699979.677361.90729990.285351.823510000.89350.8179 10011.5351.7889
10022.11354.706410043.33362.500110053.94362.438210117.59366.066410212.66368.6407
10223.12370.076110233.57 370.32610244.03371.472410254.49374.840110264.94375.8603
 10275.4379.176510317.22380.3204   10340382.054310351.44385.233510388.89 387.509
#Mann= 3 , 0 , 0
9772.646  0.0426       09772.646  0.0426       010388.89  0.0426       0
#XS Ineff= 2 , 0
       0                               0
Bank Sta=9772.646,10388.89
Exp/Cntr=0.3,0.1

Type RM Length L Ch R = 1 ,23862.13,257.820500,257.820500,257.820500
XS GIS Cut Line= 6
855579.540997861764910.838661461855653.177939123 764823.68814359
 855730.01405613764703.825966238855801.820802491764634.961559082
855862.473351405764519.221504806855888.236027347764479.649258027
#Sta/Elev= 30
9693.371385.9567 9730.35 384.7059742.598382.21699768.263372.66249793.413366.5887
9805.988364.44389829.674361.86639841.465362.18259853.257360.58419867.693355.5508
 9876.84 351.6229888.631351.14049924.119358.82379962.068360.17969972.132358.5099
9985.661350.40549991.453349.17329998.342348.749910011.04350.600910039.37369.2192
10049.92375.150810056.21376.963710095.81379.460310107.01379.0764 10119.7381.2463
10129.42380.632610140.62 381.30710180.69386.359110209.59394.082310227.91395.0239
#Mann= 3 , 0 , 0
9693.371  0.0734       09693.371  0.0734       010227.91  0.0734       0
#XS Ineff= 2 , 0
       09942.393                       0
Bank Sta=9693.371,10227.91
Exp/Cntr=0.3,0.1

Type RM Length L Ch R = 1 ,23604.31,277.875900,277.875900,277.875900
XS GIS Cut Line= 2
855841.680316076764915.842970198856119.228339878 764566.06796761
#Sta/Elev= 30
9739.628380.49339766.236379.37179804.533 373.0819868.362360.60099889.759359.1503
9906.659 361.2279919.425358.92869932.191357.88339944.956355.69659957.722 355.027
9970.198353.48159983.254347.62169986.286346.7979 9996.02346.729310008.79348.3184
10018.46352.917610021.55354.867510034.55 366.03110047.08371.617110059.85374.2265
10066.73376.783110072.61 380.05510085.38382.735710098.15 389.22710110.91390.9801
10136.44392.007210149.21394.086710161.97400.691510174.74402.656610186.14402.9239
#Mann= 3 , 0 , 0
9739.628    0.12       09739.628    0.12       010186.14    0.12       0
#XS Ineff= 2 , 0
       0                               0
Bank Sta=9739.628,10186.14
Exp/Cntr=0.3,0.1

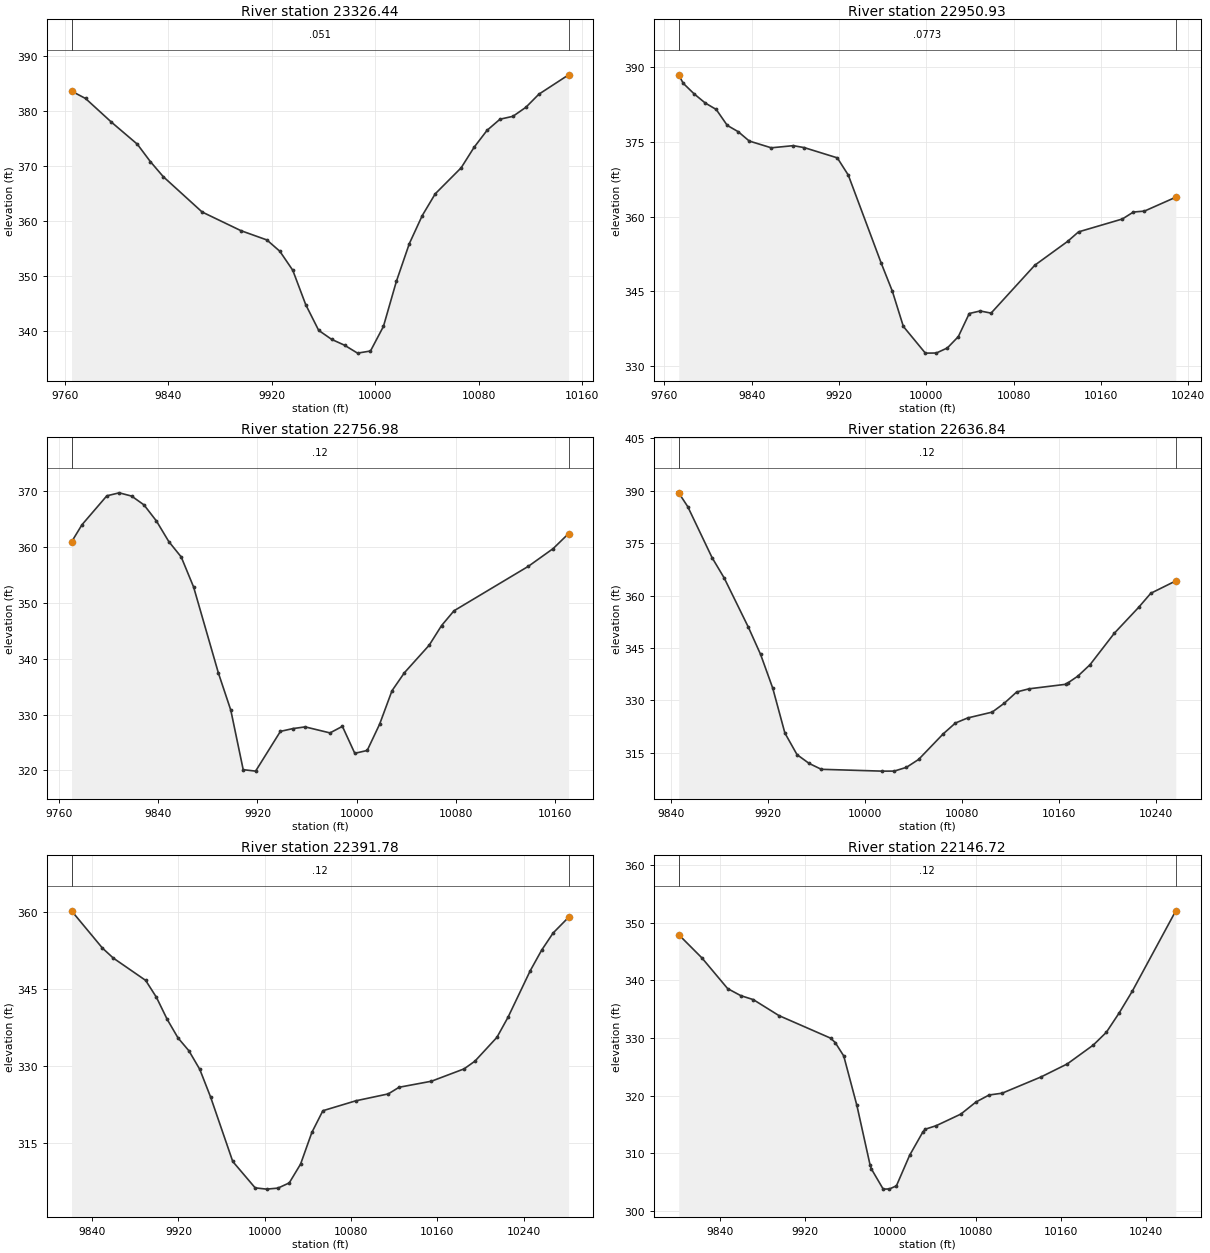
Type RM Length L Ch R = 1 ,23326.44,375.503000,375.503000,375.503000
XS GIS Cut Line= 2
855864.180360928764977.430508789856247.967035265764958.131522451
#Sta/Elev= 30
 9765.05383.61169775.883382.27869795.908 377.9689815.934 373.9599825.946 370.811
9835.959368.05779865.997361.62899896.035358.2315 9916.06356.54529926.073354.4916
9936.085351.03179946.098344.77919956.111340.10269966.123338.46349976.136337.3951
9986.148335.95959996.161336.345710006.17 340.81810016.19349.0216 10026.2355.8831
10036.21360.990510046.22364.936410066.25369.665610076.26373.397910086.27376.4821
10096.29378.5065 10106.3379.032210116.31380.675710126.33383.054210149.32386.5776
#Mann= 3 , 0 , 0
 9765.05   0.051       0 9765.05   0.051       010149.32   0.051       0
#XS Ineff= 2 , 0
       0                               0
Bank Sta=9765.05,10149.32
Exp/Cntr=0.3,0.1

Type RM Length L Ch R = 1 ,22950.93,193.954800,193.954800,193.954800
XS GIS Cut Line= 5
855790.886491588 765323.74427015856040.613970849765291.720056387
856098.728214744765293.289830532856180.190612553 765289.06609236
856243.477767412765280.350022659
#Sta/Elev= 30
9773.238388.49259777.386386.79129787.467384.64999797.549 382.8349807.631381.5334
9817.713378.34349827.795377.06739837.877375.19879858.041373.83799878.204374.2701
9888.286373.87519918.532371.82149928.614368.3516 9958.86  350.629968.941345.0535
9979.023337.97639999.187332.610610009.27332.632510019.35333.6507 10029.4335.9269
 10039.4340.566810049.41341.075210059.41340.644810099.44  350.2610129.48355.0428
10139.49356.955810179.67359.545910189.76360.941410199.86361.1278 10228.6363.9195
#Mann= 3 , 0 , 0
9773.238  0.0773       09773.238  0.0773       0 10228.6  0.0773       0
#XS Ineff= 2 , 0
       0                               0
Bank Sta=9773.238,10228.6
Exp/Cntr=0.3,0.1

Type RM Length L Ch R = 1 ,22756.98,120.140200,120.140200,120.140200
XS GIS Cut Line= 2
855816.537030898765478.250155022856217.438122527765481.336760712
#Sta/Elev= 30
9770.049360.93499778.512 364.0259798.512369.19619808.513369.73449818.513369.1521
9828.513367.57039838.514364.69349848.514361.00039858.514358.24769868.515  352.86
9888.515337.44949898.515330.79489908.516320.14159918.516319.88119938.517327.0001
9948.517327.49889958.517327.80599978.518326.72739988.518 327.9049998.518323.0706
10008.52323.583610018.52 328.28110028.52334.283310038.52337.504510058.52342.4426
10068.52 345.96410078.52348.603310138.52356.575410158.52359.748710170.96362.4339
#Mann= 3 , 0 , 0
9770.049    0.12       09770.049    0.12       010170.96    0.12       0
#XS Ineff= 2 , 0
       09923.768                       0
Bank Sta=9770.049,10170.96
Exp/Cntr=0.3,0.1

Type RM Length L Ch R = 1 ,22636.84,245.058900,245.058900,245.058900
XS GIS Cut Line= 6
855837.537084247765577.318891573855989.961530764765581.940497103
856014.824421233765582.450776949856157.212519307765602.535983242
856212.184497344765605.903564748 856245.58075773765605.486793511
#Sta/Elev= 30
9846.506389.36799853.972385.41429873.981370.85259883.986365.02059903.995350.8804
9913.999343.14519924.004333.50149934.009320.66889944.013314.48859954.018311.9717
9964.022310.296610014.04309.774310024.05309.780610034.15310.850810044.24313.1248
10064.44320.421310074.54323.533210084.64324.982910104.84326.652510114.94329.2285
10125.04332.417410135.14333.311810165.43334.607910167.67335.110410175.47336.9534
10185.49340.221810205.53349.228810225.56356.625510235.56360.643610256.14 364.182
#Mann= 3 , 0 , 0
9846.506    0.12       09846.506    0.12       010256.14    0.12       0
#XS Ineff= 2 , 0
       0                               0
Bank Sta=9846.506,10256.14
Exp/Cntr=0.3,0.1

Type RM Length L Ch R = 1 ,22391.78,245.058800,245.058800,245.058800
XS GIS Cut Line= 6
855806.400644593765803.454380358855940.155486313765805.986396223
856022.924359658 765830.83744958856097.093853382765841.556093219
856185.835885817 765834.32997876856258.454969264765812.699844211
#Sta/Elev= 30
9820.847360.22519849.511352.95419859.534 351.0159889.561 346.6559899.563343.3517
9909.565339.03779919.596335.42129929.674332.91839939.752329.2904 9949.83323.8573
9970.302311.32519991.073306.179310001.65305.930110012.16306.126710022.67307.1431
10033.18310.814210043.63 316.99310053.83 321.22510084.36323.160910114.47324.5084
10124.48325.803410154.48326.982410184.73329.389210194.81   330.910215.18 335.544
10225.47339.462710246.07 348.54510256.63352.551710267.29355.907510281.63358.9685
#Mann= 3 , 0 , 0
9820.847    0.12       09820.847    0.12       010281.63    0.12       0
#XS Ineff= 2 , 0
       0                               0
Bank Sta=9820.847,10281.63
Exp/Cntr=0.3,0.1

Type RM Length L Ch R = 1 ,22146.72,245.058900,245.058900,245.058900
XS GIS Cut Line= 6
855886.826586773766157.573249744855995.395789839766084.540974786
856051.300770473766043.894734181856121.032136154765992.086497926
856234.142196865765912.246941717856267.572757145765887.094527804
#Sta/Elev= 30
9801.033347.93839822.936343.8868 9847.04338.57779859.393337.35529871.144336.6676
9895.248333.89499943.757329.98379948.099 329.2239956.123326.89169968.489318.2986
9980.855307.98969982.098307.29139993.221303.78719999.098 303.82110005.61304.3519
10018.07309.666810030.52313.719410032.68314.183110042.98314.790710066.22316.8111
10080.36318.899910092.73 320.12110104.97320.430210141.69323.266110166.17325.5086
10190.65328.786510202.89330.994710215.13334.405810227.39338.162310268.16352.0723
#Mann= 3 , 0 , 0
9801.033    0.12       09801.033    0.12       010268.16    0.12       0
#XS Ineff= 2 , 0
       0                               0
Bank Sta=9801.033,10268.16
Exp/Cntr=0.3,0.1

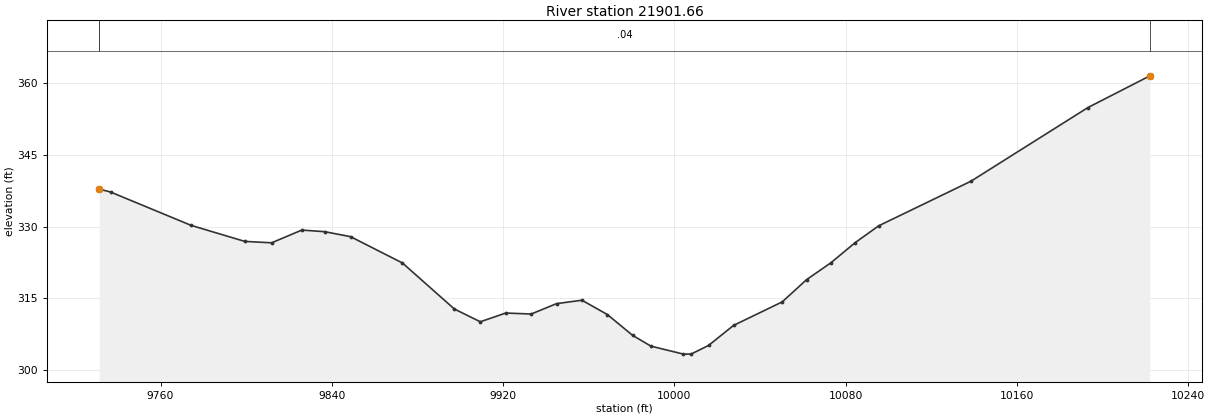
Type RM Length L Ch R = 1 ,21901.66,245.058900,245.058900,245.058900
XS GIS Cut Line= 6
856077.681876216766429.041059801856135.311291271766353.358926633
856183.210495561766283.433248041856244.560330366766186.276021902
856296.000523796766083.780850706856325.514149607766008.129002816
#Sta/Elev= 30
9731.357337.87379736.643337.26329774.305330.2808 9799.37 326.9329811.903326.6399
9825.976329.30159836.624328.96759848.745327.92479872.987322.4195 9897.23312.7965
9909.351310.12219921.249311.95419933.105311.74619944.961313.91719956.817314.6325
9968.673311.64289980.529307.2695 9989.04305.029510004.23 303.35910007.81 303.373
10015.94305.168410027.61309.359110050.36314.283210061.73318.9318 10073.1322.4643
10084.34326.638410095.38330.184910138.53339.522410193.16354.929910222.09361.5592
#Mann= 3 , 0 , 0
9731.357    0.04       09731.357    0.04       010222.09    0.04       0
#XS Ineff= 2 , 0
       09951.004                       0
Bank Sta=9731.357,10222.09
Exp/Cntr=0.3,0.1