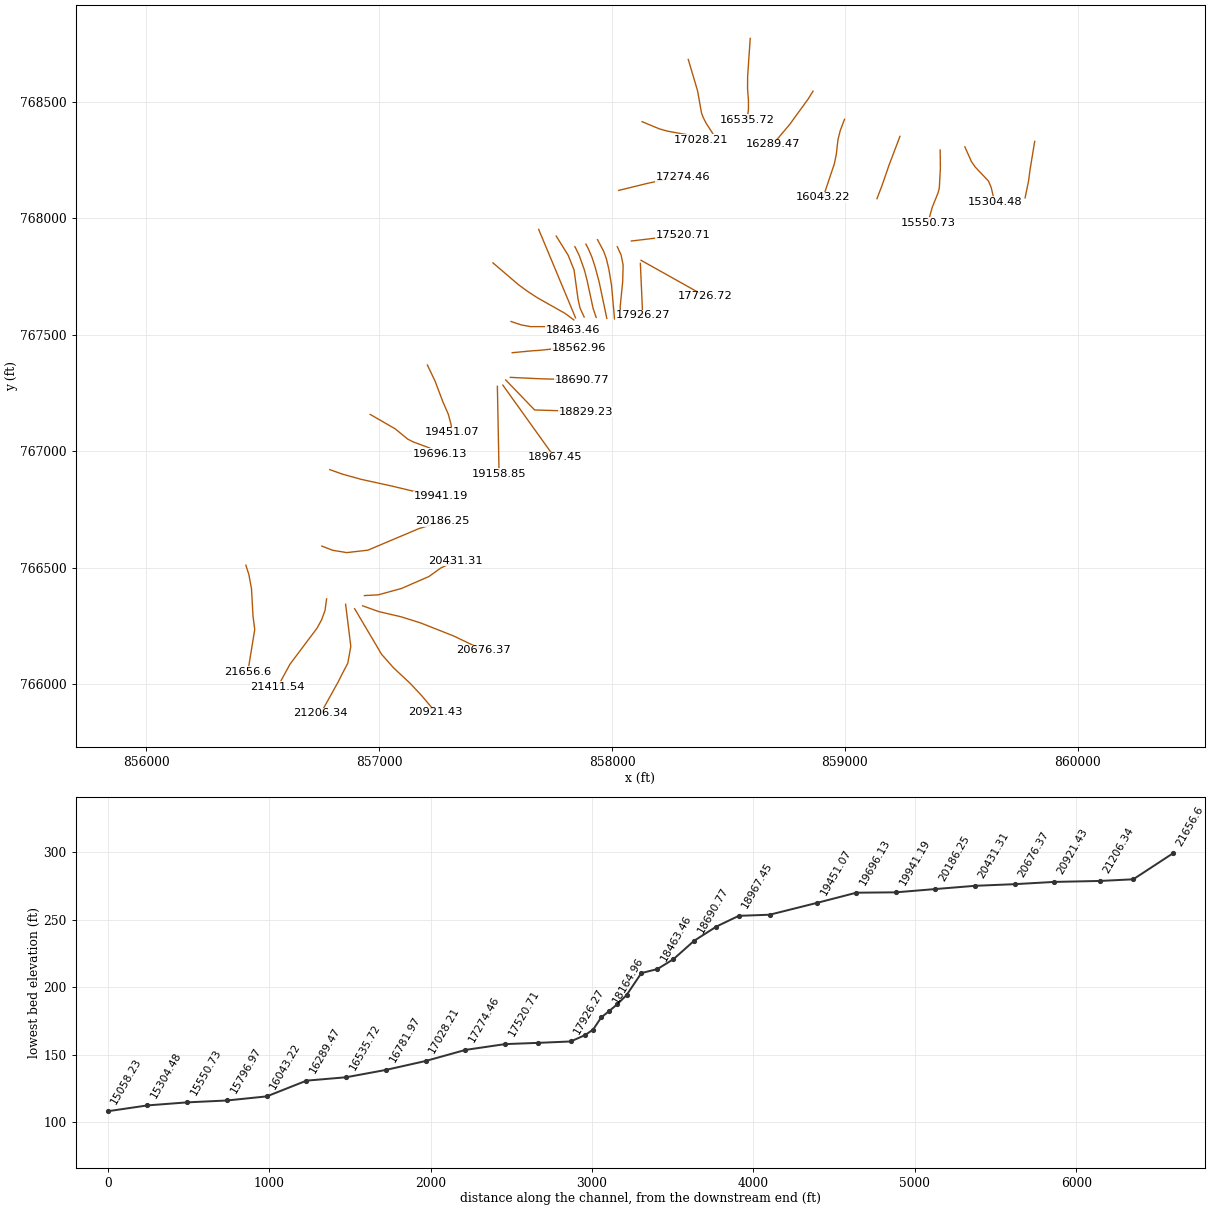
HEC-RAS study 9783_ras.prj: 9783

--- 9783_ras.g01 (geometry) --- (continued)

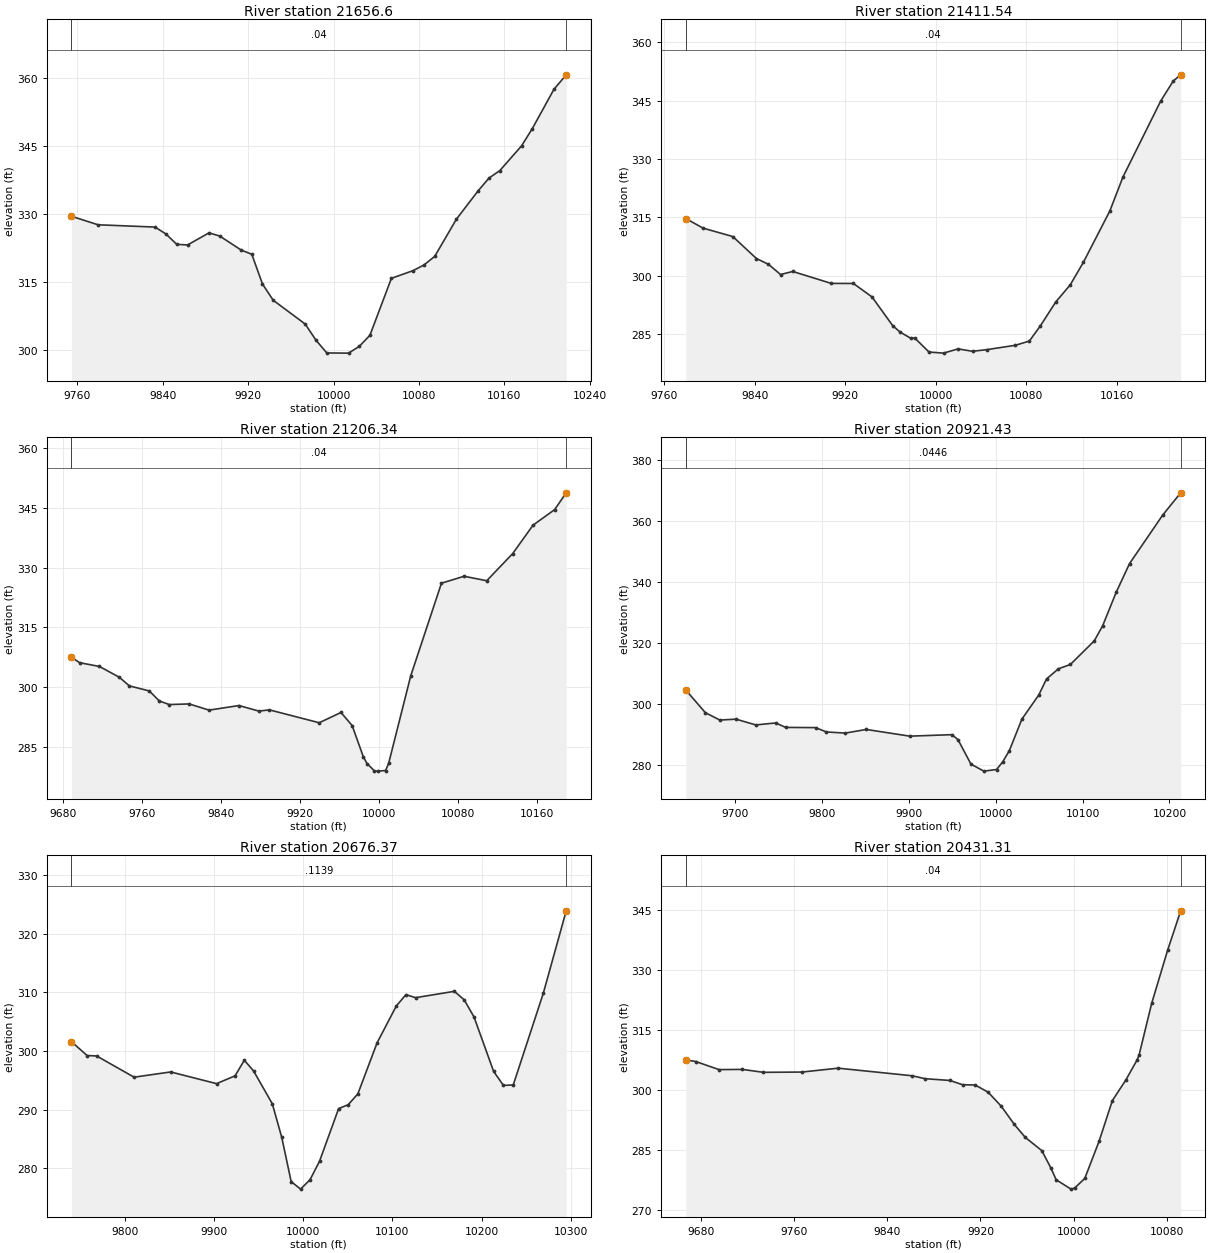
Type RM Length L Ch R = 1 , 21656.6,245.058900,245.058900,245.058900
XS GIS Cut Line= 6
856427.418118653766510.780715141856440.132642346766470.868712812
856451.555829776766409.668923599856458.071447897766292.162097406
 856465.51221207766234.532296403856435.933315406766053.596495696
#Sta/Elev= 30
 9754.32 329.4859779.298327.60649832.696327.10099842.869325.58279853.042323.2895
9863.153323.16099883.233325.82569893.273325.12389913.312322.04329923.319321.1015
9933.325314.55079943.332 310.9799973.351305.72389983.453302.16059993.593299.3538
10013.98299.313510023.99300.802210033.99303.245810054.11315.804510074.32317.4922
10084.49318.726410094.67320.633510115.01328.845110135.35335.090410145.52337.9024
 10155.7339.5573   10176344.991610186.11348.806810206.34357.454110217.87360.6635
#Mann= 3 , 0 , 0
 9754.32    0.04       0 9754.32    0.04       010217.87    0.04       0
#XS Ineff= 2 , 0
       0                               0
Bank Sta=9754.32,10217.87
Exp/Cntr=0.3,0.1

Type RM Length L Ch R = 1 ,21411.54,205.201400,205.201400,205.201400
XS GIS Cut Line= 6
856774.081213964766366.065188677856767.285484207766315.929446952
856752.631746382766276.507310116856733.492141438766241.046507391
856617.028178497766086.079049744 856564.28005745 765989.09769757
#Sta/Elev= 30
9779.071314.66819794.278312.2149 9820.57310.05139841.451304.4082 9852.12302.9206
9862.788300.29679873.562301.07639907.653298.0142 9927.22297.9925 9943.67294.5384
9961.961287.16099968.595285.4891 9978.08283.89929981.345284.01519994.095280.3764
10006.91280.097610019.76281.185310032.62280.570310045.48281.0035 10070.5282.1159
10082.81283.197310092.43287.0418 10106.1293.211610119.02297.657810130.69303.4814
10154.01316.633310165.67325.401910199.06344.913810210.12350.029810216.64351.6036
#Mann= 3 , 0 , 0
9779.071    0.04       09779.071    0.04       010216.64    0.04       0
#XS Ineff= 2 , 0
       09937.068        10080.71       0
Bank Sta=9779.071,10216.64
Exp/Cntr=0.3,0.1

Type RM Length L Ch R = 1 ,21206.34,284.916300,284.916300,284.916300
XS GIS Cut Line= 6
856855.787809616766343.191821594856878.180200018766162.228252667
856865.090094592766089.943581233856839.081251293766040.419150344
856822.911373318766008.069676318856748.705316282765874.745659814
#Sta/Elev= 30
9688.847307.52949697.101306.13239717.253305.17589737.406302.45339747.482300.2964
9767.635299.02929777.711296.51799787.787295.6065 9807.94 295.7629828.092294.2045
9858.321295.36029878.536293.95499889.037294.27459939.512291.02899961.529293.6137
9972.824290.32719984.119282.48239987.863280.78769995.414278.91289998.589278.8717
10006.65279.018310009.72280.802810032.08302.819610063.16326.110610086.05327.8537
10108.94326.727110135.27333.572910155.83340.7042 10177.6344.598210189.34348.8256
#Mann= 3 , 0 , 0
9688.847    0.04       09688.847    0.04       010189.34    0.04       0
#XS Ineff= 2 , 0
       09900.946                       0
Bank Sta=9688.847,10189.34
Exp/Cntr=0.3,0.1

Type RM Length L Ch R = 1 ,20921.43,245.058900,245.058900,245.058900
XS GIS Cut Line= 6
856894.482237834766324.068071584857010.396963297766128.087358587
857062.180953316766069.662774979857132.447433269766004.175755953
857180.945972792765952.477827182857243.028519634765879.329647674
#Sta/Elev= 30
9643.995304.63839666.408 297.2789683.033294.86219701.602295.1543 9724.46293.2655
9747.319293.91479758.748292.45499793.036292.38949805.565290.96649827.324290.6004
9851.378291.78579901.458289.5966 9949.97290.08329956.891288.42199971.735280.4525
 9986.58 278.15310001.22278.683710008.22281.191510015.76284.7703 10030.3295.1608
10049.76303.078610058.61308.306310072.33311.631810086.04 313.04310113.46 320.747
10123.18325.721910138.64336.607410154.09346.061610192.31361.966110212.86 369.202
#Mann= 3 , 0 , 0
9643.995  0.0446       09643.995  0.0446       010212.86  0.0446       0
#XS Ineff= 2 , 0
       09813.894                       0
Bank Sta=9643.995,10212.86
Exp/Cntr=0.3,0.1

Type RM Length L Ch R = 1 ,20676.37,245.058900,245.058900,245.058900
XS GIS Cut Line= 6
856929.147732397766336.317058067856997.940170748766311.617734674
857094.266108986766289.181562533857178.659608932766262.658229901
857320.263264952766206.736385139857447.847106571766145.594024827
#Sta/Elev= 30
9740.351 301.6159757.885299.25089768.647299.17159810.546295.55829851.663296.4474
9903.002 294.4559923.699295.78799934.117298.44349944.536 296.6039965.467291.0259
9976.031285.31239986.595277.76399997.159276.481810007.77278.095110018.44281.2572
10039.78290.211110050.54290.869110061.33292.721210082.89301.419310104.45307.7024
10115.24309.623810126.02309.106510169.46310.187710180.46308.737910191.45 305.825
10213.44296.543810224.44  294.1610235.43294.227810269.06309.836210294.77323.9041
#Mann= 3 , 0 , 0
9740.351  0.1139       09740.351  0.1139       010294.77  0.1139       0
#XS Ineff= 2 , 0
       09944.517        10077.91       0
Bank Sta=9740.351,10294.77
Exp/Cntr=0.3,0.1

Type RM Length L Ch R = 1 ,20431.31,245.058800,245.058800,245.058800
XS GIS Cut Line= 6
856936.548043279766380.284956791856996.592507983766383.626259214
857095.542600449766410.695471157857213.466051699766462.022237789
857264.306799408766498.472365896857328.093649074766529.242280456
#Sta/Elev= 30
9666.829307.5974 9675.31307.18679695.313305.16519715.426305.2105 9733.45304.4841
9766.444304.55029797.738305.52239861.509303.61639872.276302.8955 9893.81302.4434
9904.576301.38259915.467301.31219926.657299.49369937.848296.00779949.038291.4783
9958.512288.19359972.731284.88519980.703280.43179985.059277.60389997.802 275.259
   10001275.548210009.64277.942610021.87287.194110033.36297.428910044.86302.5354
10054.57307.566610056.33308.852410067.12321.738310080.76334.969610092.04344.8907
#Mann= 3 , 0 , 0
9666.829    0.04       09666.829    0.04       010092.04    0.04       0
#XS Ineff= 2 , 0
       0                               0
Bank Sta=9666.829,10092.04
Exp/Cntr=0.3,0.1

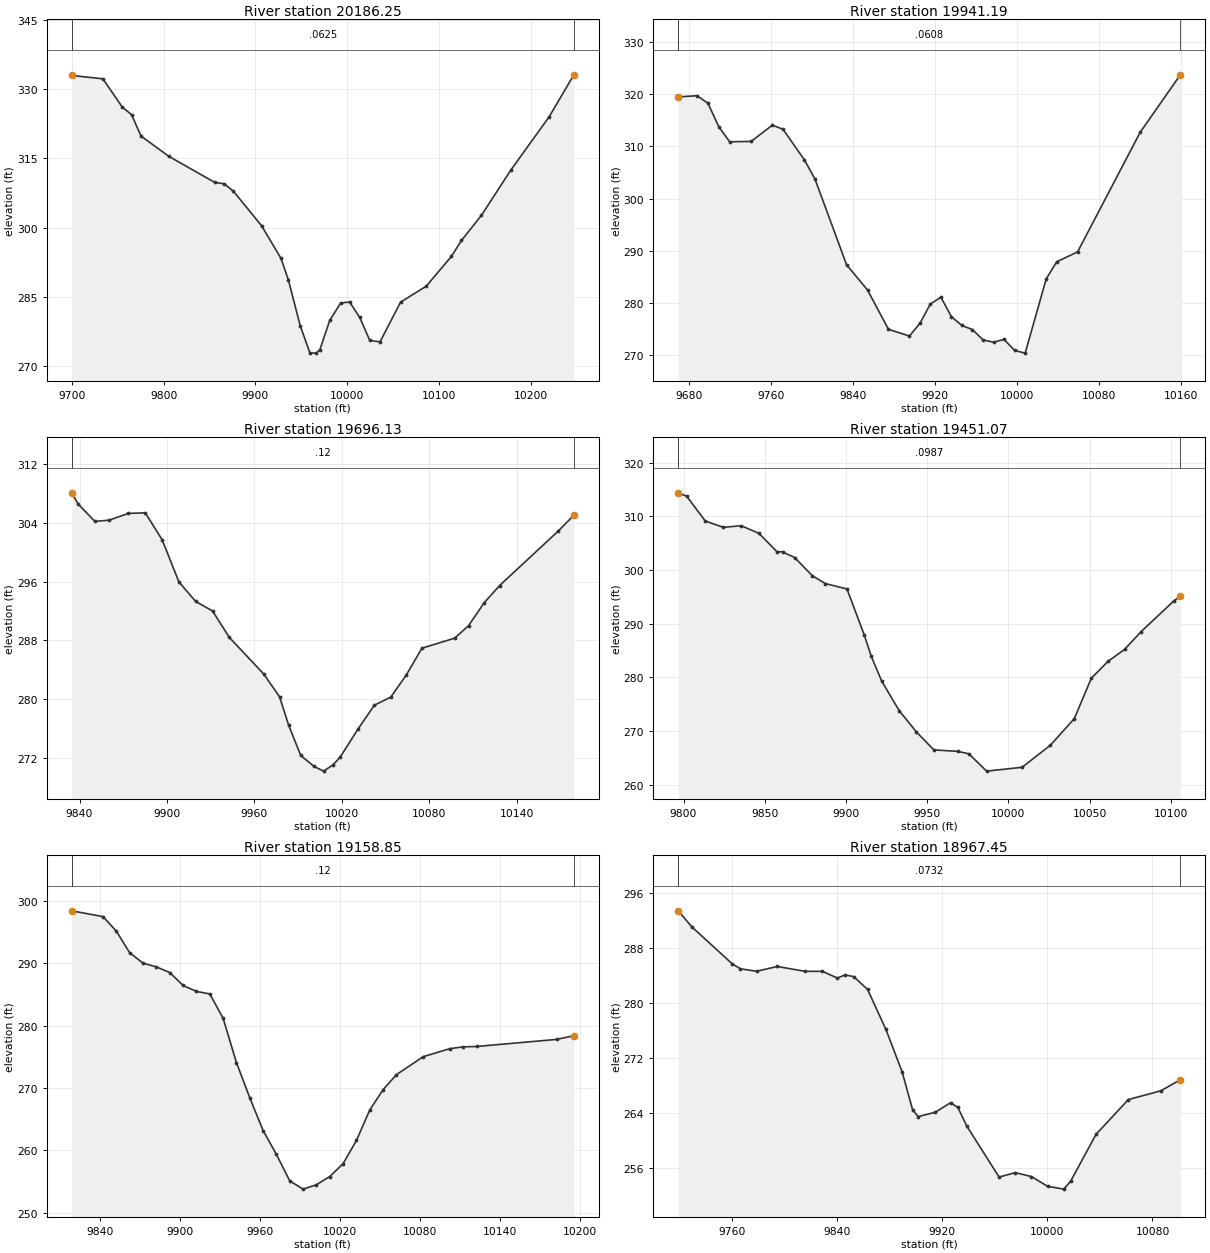
Type RM Length L Ch R = 1 ,20186.25,245.058900,245.058900,245.058900
XS GIS Cut Line= 6
856753.736259988766592.686641587  856800.0111414766574.668494073
856861.079453869766564.749625713856951.363694822 766575.13811374
857170.250382701766667.520125916857271.080780127766698.523277942
#Sta/Elev= 30
9700.104332.95059733.961332.23019754.946326.14549765.235 324.4519775.459319.8428
9805.665315.45869855.748309.80559865.885309.51869876.066307.89619906.719300.4131
9927.686 293.4139935.766288.76349948.652278.84299959.289272.91089966.056272.8666
9970.072273.59099980.855279.95439992.784  283.7210002.48283.926210013.44280.6159
 10024.4275.624910035.56275.304610057.87283.886210085.93287.366210113.29293.8142
10124.21297.247810145.92302.684210177.88312.469110219.61324.010210246.49333.0908
#Mann= 3 , 0 , 0
9700.104  0.0625       09700.104  0.0625       010246.49  0.0625       0
#XS Ineff= 2 , 0
       0                               0
Bank Sta=9700.104,10246.49
Exp/Cntr=0.3,0.1

Type RM Length L Ch R = 1 ,19941.19,245.058900,245.058900,245.058900
XS GIS Cut Line= 6
856787.662828075766920.836858279856841.104790913766901.779079007
856922.127480211766879.213434904857053.814868218766850.438238005
857147.534031527  766827.9945723857263.575863093766806.647413671
#Sta/Elev= 30
9669.517319.49499687.924319.71199698.541318.26799709.157313.74939719.774310.8918
 9740.68310.96679761.441314.09139771.821 313.2779792.583307.45179802.963303.7703
9833.774287.35489854.246282.51149874.718274.9735 9895.19273.70079905.426 276.138
9915.662279.84789925.898281.11599936.134277.40639946.376275.71419956.664274.9298
9966.953272.96379977.242272.5118 9987.53273.04929997.819270.9347 10008.1270.4232
10028.65284.641210038.92287.915510059.29289.815110120.29  312.6910159.52323.7169
#Mann= 3 , 0 , 0
9669.517  0.0608       09669.517  0.0608       010159.52  0.0608       0
#XS Ineff= 2 , 0
       09918.013                       0
Bank Sta=9669.517,10159.52
Exp/Cntr=0.3,0.1

Type RM Length L Ch R = 1 ,19696.13,245.058900,245.058900,245.058900
XS GIS Cut Line= 6
856961.262438943767157.737085125857068.189202447 767096.20699075
857122.748712489767051.608419594857146.130440888767039.746855609
857214.825989222 767014.38844481857259.294308752766989.216899588
#Sta/Elev= 30
9834.695308.11539839.008306.60169850.545304.22079860.233304.3832 9873.62305.3107
9885.157305.38449896.695301.72039908.232295.9573 9919.77293.28969931.307292.0024
9942.845288.38399966.441283.39739977.299280.29419983.474276.45859991.823272.2831
   10001270.7867 10007.5270.147510013.91270.983710018.92272.066210031.19275.8992
 10042.4 279.14710053.62280.240810064.34283.2785   10075286.914310097.47288.2903
10106.98289.976310117.64293.0906 10128.3295.459310168.58302.902410179.28 305.062
#Mann= 3 , 0 , 0
9834.695    0.12       09834.695    0.12       010179.28    0.12       0
#XS Ineff= 2 , 0
       0                               0
Bank Sta=9834.695,10179.28
Exp/Cntr=0.3,0.1

Type RM Length L Ch R = 1 ,19451.07,292.228300,292.228300,292.228300
XS GIS Cut Line= 6
857206.989697043767369.566069611857239.735275187767301.379939688
857273.821876788767211.185825397 857296.71908569767159.001515337
857308.752539146767114.623118761857312.884020104767080.947255516
#Sta/Elev= 30
9796.749314.35969801.967313.72269813.395309.11419824.511307.93269835.497308.2397
9846.484306.80789857.471303.41539861.004303.35459868.458302.30819879.256298.9384
9887.328297.46899900.636 296.4629911.327287.84369915.615283.89759922.017279.3054
9932.707273.84099943.398269.83689954.088266.51479968.856266.23379975.633265.7844
9986.588262.559510008.42263.274910025.85267.387310040.56272.326910051.02279.8391
10061.26282.979710071.49285.209810081.57288.492410101.72294.213610105.81295.1155
#Mann= 3 , 0 , 0
9796.749  0.0987       09796.749  0.0987       010105.81  0.0987       0
#XS Ineff= 2 , 0
       0                               0
Bank Sta=9796.749,10105.81
Exp/Cntr=0.3,0.1

Type RM Length L Ch R = 1 ,19158.85,191.393800,191.393800,191.393800
XS GIS Cut Line= 2
857507.574901589767278.463397798 857514.95603682766902.016007301
#Sta/Elev= 30
9818.847298.37619842.315297.44699852.317 295.1089862.319291.65319872.321289.9936
9882.323289.39699892.325288.49439902.327286.42139912.329285.46499922.331 285.071
9932.333281.17389942.334274.07919952.336268.42739962.338263.1815 9972.34 259.347
9982.342  255.119992.344253.799810002.35254.504210012.35 255.82210022.35257.8899
10032.35 261.60210042.35266.486310052.36269.739310062.36272.137210082.36275.0068
10102.37276.300210112.37276.587810122.37276.646210182.38277.778710195.37278.3754
#Mann= 3 , 0 , 0
9818.847    0.12       09818.847    0.12       010195.37    0.12       0
#XS Ineff= 2 , 0
       0                               0
Bank Sta=9818.847,10195.37
Exp/Cntr=0.3,0.1

Type RM Length L Ch R = 1 ,18967.45,138.225400,138.225400,138.225400
XS GIS Cut Line= 2
857531.076917724 767283.45900398 857753.62442763766972.899406919
#Sta/Elev= 30
9719.121293.35039729.528291.01299760.192 285.6659766.435284.94029778.738284.5834
9794.528285.27369815.645284.57119828.863284.56969840.251283.59159846.031 284.061
9852.553283.80839863.199281.94929877.158276.14179889.461270.01339897.535264.4457
9901.763263.49729914.703264.12519926.368265.50139931.871264.83469938.671262.1326
9963.276254.72179975.578255.36139987.881254.798710000.18253.383210012.49252.9719
10017.71 254.11110037.09260.9279 10061.7265.970110086.38267.236110101.19 268.846
#Mann= 3 , 0 , 0
9719.121  0.0732       09719.121  0.0732       010101.19  0.0732       0
#XS Ineff= 2 , 0
       0                               0
Bank Sta=9719.121,10101.19
Exp/Cntr=0.3,0.1

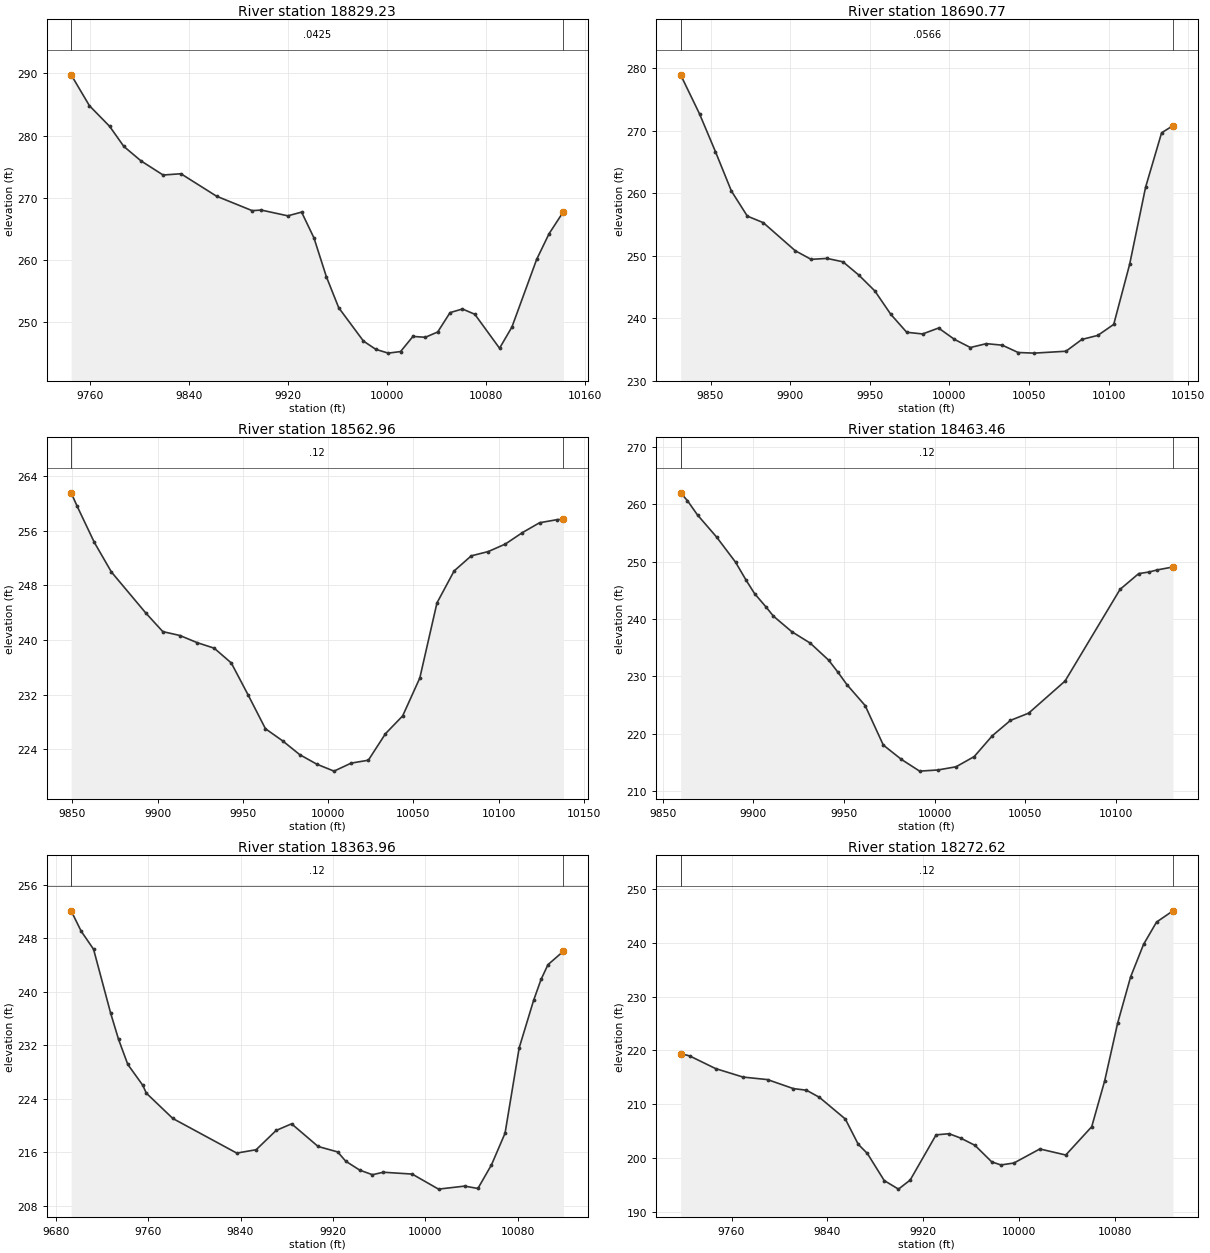
Type RM Length L Ch R = 1 ,18829.23,138.455300,138.455300,138.455300
XS GIS Cut Line= 3
857543.384457551767305.643256178857667.570692808767176.855896484
857886.679501445767170.168962659
#Sta/Elev= 30
9744.677289.77159759.462284.80479775.817281.48359787.246278.26819801.138275.9409
9819.037273.66499833.443273.87049862.256270.26019891.069 267.937 9898.38268.0328
9919.882267.10619931.019267.70199941.023263.55339951.028257.33189961.033252.3337
9981.042246.97199991.047245.642810001.05245.034710011.06245.288110021.06247.7196
10031.07247.581610041.07248.432910051.07251.547210061.08252.129410071.08 251.284
10091.09245.8189 10101.1249.232310121.11260.109210131.11264.2233 10142.8267.7931
#Mann= 3 , 0 , 0
9744.677  0.0425       09744.677  0.0425       0 10142.8  0.0425       0
#XS Ineff= 2 , 0
       0                10076.82       0
Bank Sta=9744.677,10142.8
Exp/Cntr=0.3,0.1

Type RM Length L Ch R = 1 ,18690.77,127.813900,127.813900,127.813900
XS GIS Cut Line= 6
857563.153670387767316.778510347857692.111654107767310.717908474
857736.673985917 767309.50869854 857738.67332457767309.457235017
857854.005760652767307.700035695857872.102320114 767305.77332614
#Sta/Elev= 30
9831.205278.91429843.064272.67999853.075266.63689863.086260.35039873.097 256.338
9883.108255.2928 9903.13250.81839913.141249.42789923.152249.57949933.163249.0345
9943.174246.90219953.185244.38129963.194240.64769973.198237.77589983.202237.5065
9993.205238.455310003.21236.637510013.21235.341210023.21235.957210033.21235.7135
10043.21234.542910053.22234.442910073.22234.745910083.22236.629810093.22237.2768
10103.22239.032610113.22248.637510123.23260.950810133.29269.650810140.43270.7862
#Mann= 3 , 0 , 0
9831.205  0.0566       09831.205  0.0566       010140.43  0.0566       0
#XS Ineff= 2 , 0
       0                               0
Bank Sta=9831.205,10140.43
Exp/Cntr=0.3,0.1

Type RM Length L Ch R = 1 ,18562.96,99.499700,99.499700,99.499700
XS GIS Cut Line= 6
857571.482861142767422.609947134857655.538609789767430.608768646
857690.278993212767432.831063384857801.005195117767445.104542343
857827.135984713767445.544198343857858.983849003767442.772276278
#Sta/Elev= 30
9849.305261.55879852.838259.58869862.883254.30799872.928249.96369893.019243.9828
9903.064241.23939913.109240.66969923.154239.6283  9933.2238.81539943.221236.6505
9953.242231.89639963.262227.0199  9973.3225.25339983.357223.22729993.415 221.826
10003.47 220.81310013.54221.9871 10023.6  222.4110033.66 226.29610043.73228.8985
10053.79234.448210063.85 245.44110073.91250.119710083.95252.331410093.95252.9612
10103.95254.060210113.98255.737110124.02257.178610134.06257.620610138.06257.7093
#Mann= 3 , 0 , 0
9849.305    0.12       09849.305    0.12       010138.06    0.12       0
#XS Ineff= 2 , 0
       0                               0
Bank Sta=9849.305,10138.06
Exp/Cntr=0.3,0.1

Type RM Length L Ch R = 1 ,18463.46,99.499800,99.499800,99.499800
XS GIS Cut Line= 6
857566.351026083767556.539791404857611.210991242767541.633230412
 857650.05711402767534.510849926857763.482135549767534.483088905
857799.422615408767530.091970414857833.219680547767521.405896133
#Sta/Elev= 30
9859.864262.01329863.579260.66189869.198258.14229879.685254.30819890.173249.9092
9895.998246.7659 9900.66244.43079907.173242.02439911.026240.50679921.192237.7871
9931.359235.79429941.526232.81699946.667230.7045 9951.62228.54029961.641224.9037
9971.661218.00769981.681215.50199991.701213.462810001.75213.663610011.78214.2203
10021.81216.003510031.81219.643110041.82222.316810051.82223.574110071.91229.1765
10102.25245.172310112.54247.921910118.07248.190410122.84248.571110131.44249.0756
#Mann= 3 , 0 , 0
9859.864    0.12       09859.864    0.12       010131.44    0.12       0
#XS Ineff= 2 , 0
       0                               0
Bank Sta=9859.864,10131.44
Exp/Cntr=0.3,0.1

Type RM Length L Ch R = 1 ,18363.96,91.335100,91.335100,91.335100
XS GIS Cut Line= 6
857488.615242131767808.100854549857598.846781425767713.931839077
857635.794253826767686.873522144857678.394647712767658.968279022
857798.253896389767591.334794455 857835.76655371767563.404051063
#Sta/Elev= 30
9693.386252.13189702.049249.08569712.768246.38319727.563 236.8169734.384232.9026
9742.404229.13939755.403226.00689758.471224.83089781.402221.04169836.728215.8603
9853.517216.36429870.816219.24919884.196220.24239907.155216.84979924.114216.0316
9931.064214.64459943.223 213.3069954.169212.62319963.638212.9932 9988.58212.7177
10011.37210.464310034.01210.917610045.47210.563210057.22214.103310068.96218.8351
10081.19231.613210093.66 238.71410100.14241.868910106.13244.075610119.55 246.092
#Mann= 3 , 0 , 0
9693.386    0.12       09693.386    0.12       010119.55    0.12       0
#XS Ineff= 2 , 0
       0 9952.06                       0
Bank Sta=9693.386,10119.55
Exp/Cntr=0.3,0.1

Type RM Length L Ch R = 1 ,18272.62,57.914500,57.914500,57.914500
XS GIS Cut Line= 2
857684.918207597767951.992055765857843.319096011767572.336651143
#Sta/Elev= 30
 9717.48219.41959725.056 218.9779746.727216.62069769.633215.04569790.069214.5754
 9811.74212.89549822.575 212.6039833.411  211.289855.082207.24159865.917202.5256
9873.515200.82379887.588195.78829899.485194.19139909.259195.8754 9930.93204.2938
9941.765204.50469951.426203.69479963.436202.33859977.397199.26769985.107 198.691
9995.943199.049810017.61201.667610039.28200.541410060.96205.806110071.79214.3407
10082.63225.088910093.46233.6904 10104.3 239.75210115.13 243.89210128.85245.9842
#Mann= 3 , 0 , 0
 9717.48    0.12       0 9717.48    0.12       010128.85    0.12       0
#XS Ineff= 2 , 0
       09940.601                       0
Bank Sta=9717.48,10128.85
Exp/Cntr=0.3,0.1

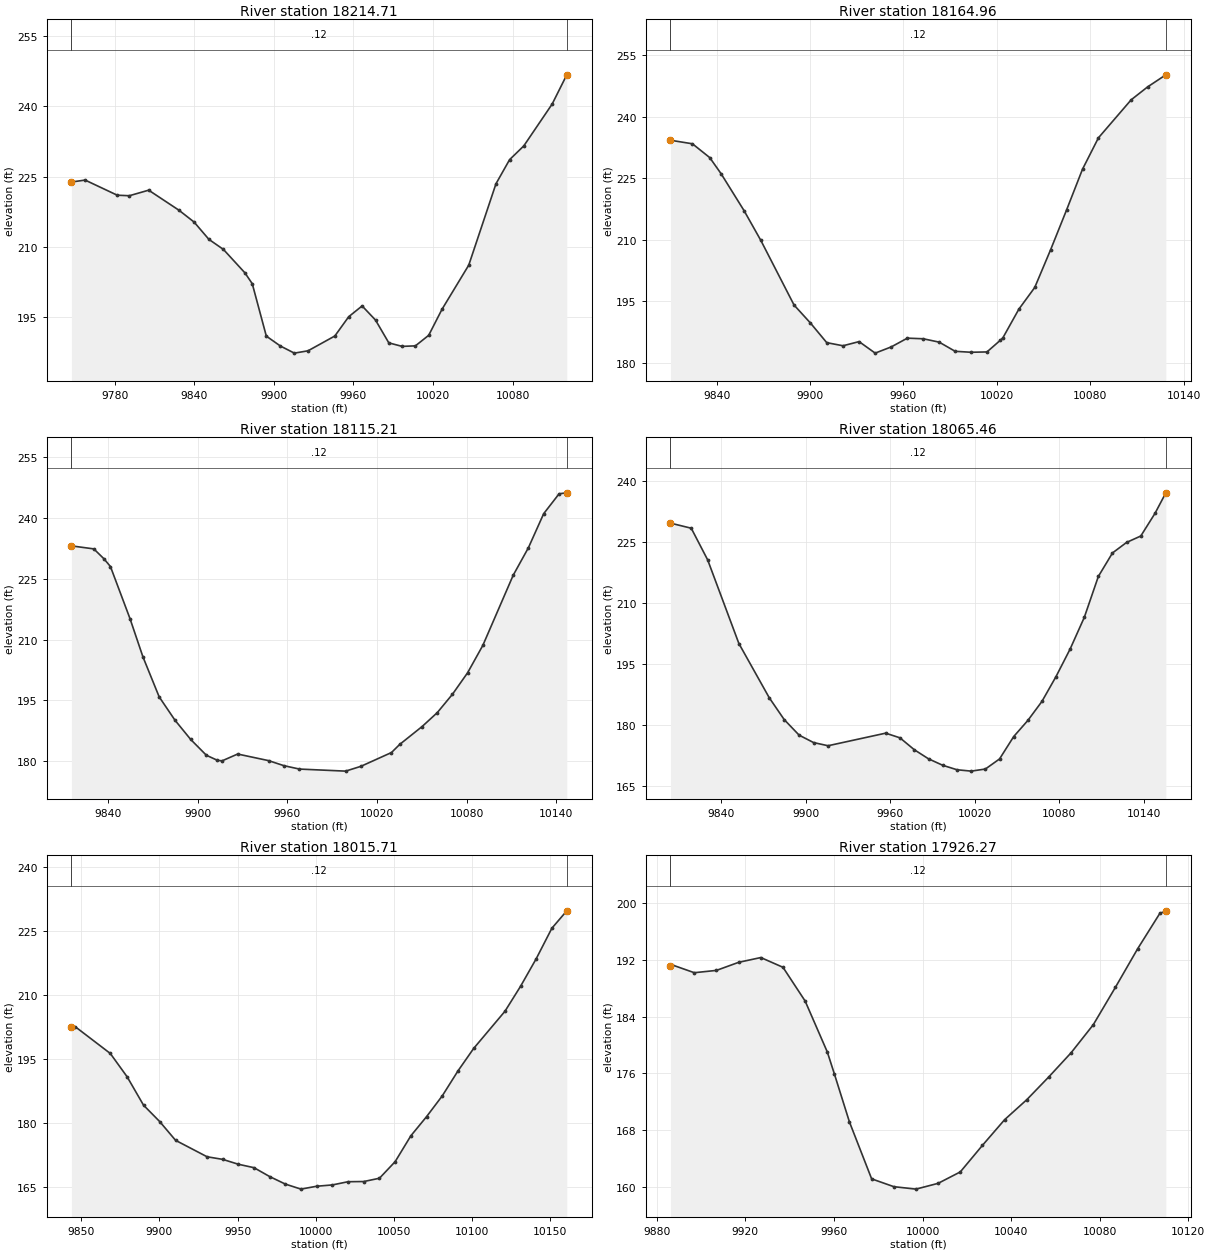
Type RM Length L Ch R = 1 ,18214.71,49.749900,49.749900,49.749900
XS GIS Cut Line= 6
857760.190822282767923.296384108857811.511375374767841.021108945
857836.802279332 767778.07064634857854.341963838 767650.29058576
857863.094473669767612.911940779857880.332965564767575.782634625
#Sta/Elev= 30
9747.207223.85439757.519224.27319781.774 221.0429790.892220.93079805.471222.1149
9828.327217.83779839.755215.30869850.906211.61959861.874209.46829878.079204.4739
9883.624202.15239894.236190.96419904.847188.85289915.366187.33459925.676187.8275
9945.919190.99079956.409195.11369966.511197.40849976.612194.39129986.648189.5236
9996.671188.7761 10006.7188.884710016.73191.137510026.76196.686510046.95206.1163
10067.49223.488410077.76228.629810088.47231.563910109.88240.5017 10120.9246.7364
#Mann= 3 , 0 , 0
9747.207    0.12       09747.207    0.12       0 10120.9    0.12       0
#XS Ineff= 2 , 0
       09883.765                       0
Bank Sta=9747.207,10120.9
Exp/Cntr=0.3,0.1

Type RM Length L Ch R = 1 ,18164.96,49.749900,49.749900,49.749900
XS GIS Cut Line= 6
857840.708317113767877.653150302857858.848997601767840.605587865
857880.892223753767778.819458002857892.343558994767735.234562953
857918.817904943767612.510968896857931.907316523767573.906271828
#Sta/Elev= 30
9810.355234.26429824.444 233.4029835.578  230.039842.853 226.108 9857.63217.0895
9868.397209.83539889.744194.06849900.247189.69569910.749184.8935 9921.19184.1338
9931.529185.14979941.868182.33849952.208183.85899962.545185.9909 9972.78185.8403
9983.016185.01559993.252182.782210003.47182.5499 10013.7182.630910022.27185.4698
10023.93186.081210034.16193.045310044.39 198.35410054.62207.584810064.85217.2684
10075.08227.199310085.31234.852810106.34244.1254 10116.9247.273510128.62250.2215
#Mann= 3 , 0 , 0
9810.355    0.12       09810.355    0.12       010128.62    0.12       0
#XS Ineff= 2 , 0
       0                               0
Bank Sta=9810.355,10128.62
Exp/Cntr=0.3,0.1

Type RM Length L Ch R = 1 ,18115.21,49.749800,49.749800,49.749800
XS GIS Cut Line= 6
857887.912226071767888.242713366857898.107459127767869.033123159
 857913.20748764767833.799521402857927.465886492 767790.54053645
857944.617214554767726.373104336857977.573640959767570.047285303
#Sta/Elev= 30
9815.245 233.0949830.238 232.3489836.993 229.9219841.381227.9938 9854.49  215.14
 9863.14205.7262 9874.02195.85879884.591190.1092 9895.12185.35819905.649181.4513
9912.997180.21019916.179 180.0729926.609  181.759947.311180.12699957.662178.8733
9968.013178.04319998.932177.535610009.17178.717510029.67182.122110035.19184.1284
10050.18188.531310060.35 191.96310070.53 196.498 10080.7201.814410090.88208.5525
10111.23225.863110121.41232.637610131.64241.034510141.98245.945110147.11246.1765
#Mann= 3 , 0 , 0
9815.245    0.12       09815.245    0.12       010147.11    0.12       0
#XS Ineff= 2 , 0
       0                               0
Bank Sta=9815.245,10147.11
Exp/Cntr=0.3,0.1

Type RM Length L Ch R = 1 ,18065.46,49.749900,49.749900,49.749900
XS GIS Cut Line= 6
857937.635527785767907.631496474857964.137995524 767857.96226367
857975.718568696767825.458134197 857986.30466138767781.350642781
 857997.76866616767712.572805013858010.853015946767567.378904579
#Sta/Elev= 30
9803.861 229.6929818.593228.43769830.255220.63819852.436200.01659873.986186.6609
9884.602 181.2779895.202 177.4389905.486175.6048 9915.77174.82449956.676177.9257
9966.819176.77549976.962173.85559987.105171.60119997.248169.998810007.37168.9036
10017.44168.5668 10027.5169.084710037.56171.570110047.62177.087810057.64181.0536
10067.66 185.74410077.68191.879610087.71  198.6810097.73206.442910107.75216.5651
10117.77222.3395 10127.8224.939910137.88226.518810147.96 232.09710155.66237.1592
#Mann= 3 , 0 , 0
9803.861    0.12       09803.861    0.12       010155.66    0.12       0
#XS Ineff= 2 , 0
       0                               0
Bank Sta=9803.861,10155.66
Exp/Cntr=0.3,0.1

Type RM Length L Ch R = 1 ,18015.71,89.440400,89.440400,89.440400
XS GIS Cut Line= 6
858022.683832996767877.204549871858039.297910371767841.184580822
858047.714791309767798.263690845858045.693322869767726.597987256
858035.046339473767620.229581782858036.573899746767565.494467757
#Sta/Elev= 30
9843.666202.44629846.198202.50789868.544196.26739879.311190.80199889.812184.1565
9900.151180.31979910.327175.91969930.495172.06859940.498171.45869950.501 170.317
9960.508169.51419970.531167.43639980.555165.67439990.578164.490110000.61165.1673
10010.66 165.47110020.71166.225910030.76166.269610040.81167.041410050.86170.9298
10060.91176.985710070.96 181.46710081.01186.336110091.06192.178310101.11197.4486
10121.13206.151810131.13212.009710141.14218.458410151.17225.6074 10160.7229.6794
#Mann= 3 , 0 , 0
9843.666    0.12       09843.666    0.12       0 10160.7    0.12       0
#XS Ineff= 2 , 0
       0                               0
Bank Sta=9843.666,10160.7
Exp/Cntr=0.3,0.1

Type RM Length L Ch R = 1 ,17926.27,199.545300,199.545300,199.545300
XS GIS Cut Line= 2
 858121.69597948767805.744253795858131.689178289767582.274196076
#Sta/Elev= 26
9886.167191.16449886.912191.28499896.922190.18479906.932190.51179916.942191.6469
9926.952192.31989936.962190.94829946.972186.19789956.982179.02749960.127175.9855
9966.992169.16589977.002161.16539987.012160.06639997.022159.719410007.03160.5352
10017.04162.142210027.05165.884910037.06169.496510047.07172.310310057.08175.5411
10067.09178.9194 10077.1 182.86610087.11188.141610097.12193.551410107.13198.5258
10109.86198.8971
#Mann= 3 , 0 , 0
9886.167    0.12       09886.167    0.12       010109.86    0.12       0
#XS Ineff= 2 , 0
       0                               0
Bank Sta=9886.167,10109.86
Exp/Cntr=0.3,0.1

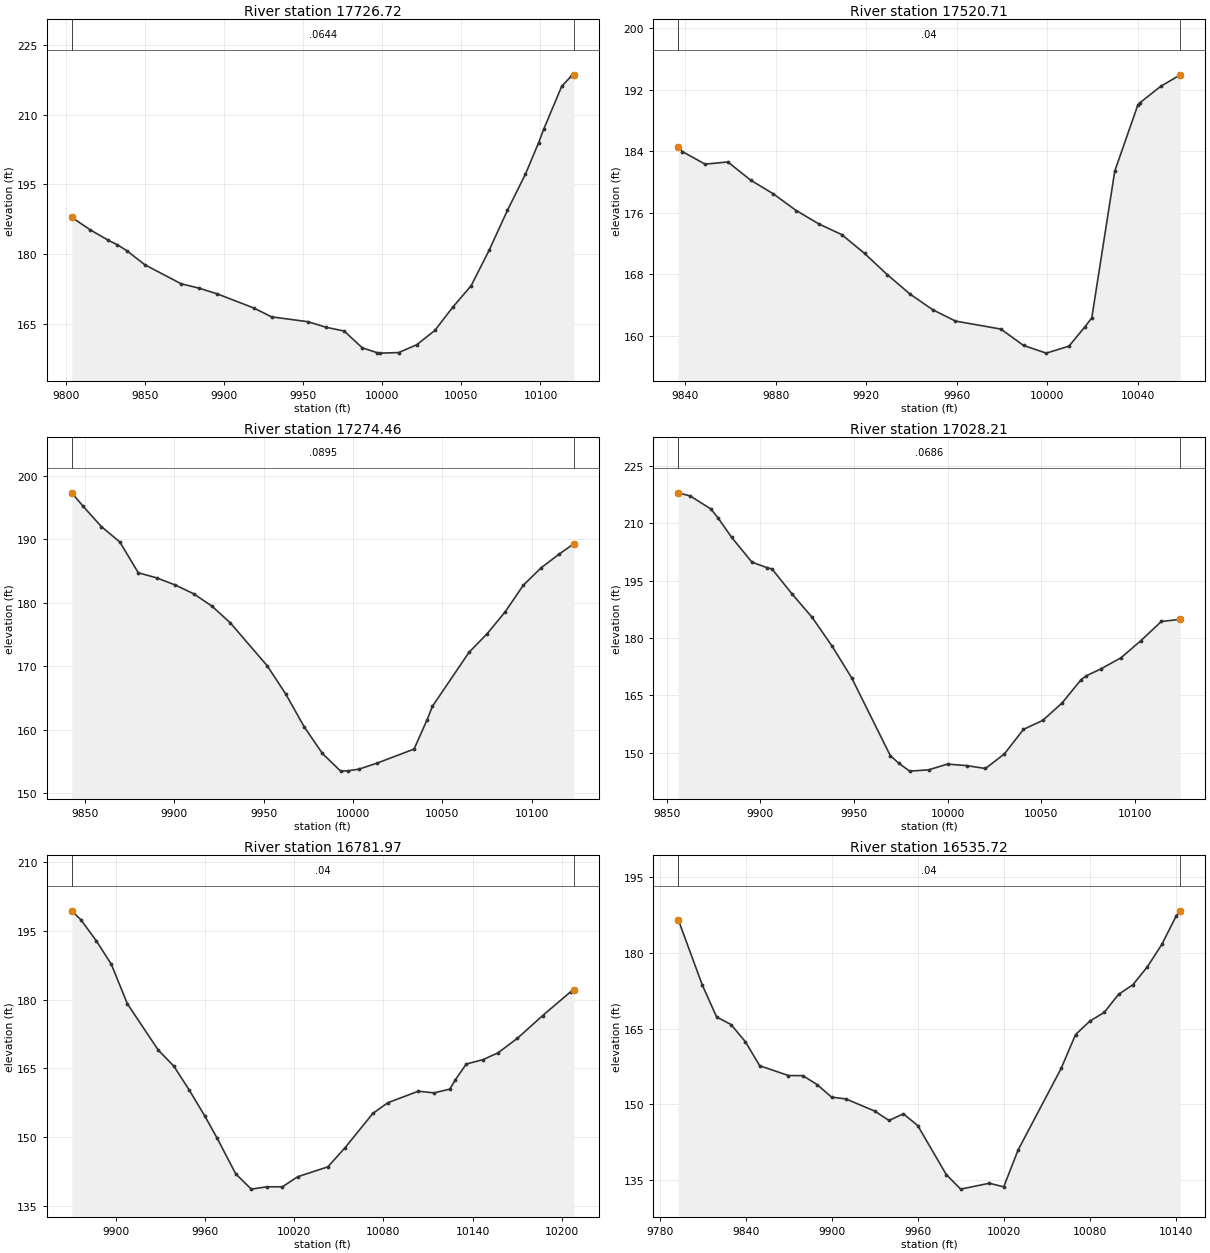
Type RM Length L Ch R = 1 ,17726.72,206.011800,206.011800,206.011800
XS GIS Cut Line= 2
858124.748036498767819.082013846858401.676382087767664.126325954
#Sta/Elev= 30
9803.762187.88849815.509185.20339826.968182.9514  9832.6182.00389838.427180.7598
9849.886177.71629872.805 173.6289884.264172.65989895.723171.44149918.641168.4253
  9930.1 166.4959953.018165.45259964.477164.25989975.936163.44429987.395159.8335
9996.432158.82459998.854158.695810010.31158.815510021.77160.494610033.23163.5722
10044.69168.634110056.15173.174810067.61180.862310079.07189.375510090.53197.2127
10098.83  203.9510101.99206.808310113.44216.096810119.31218.2192 10121.1218.5544
#Mann= 3 , 0 , 0
9803.762  0.0644       09803.762  0.0644       0 10121.1  0.0644       0
#XS Ineff= 2 , 0
       0                               0
Bank Sta=9803.762,10121.1
Exp/Cntr=0.3,0.1

Type RM Length L Ch R = 1 ,17520.71,246.248100,246.248100,246.248100
XS GIS Cut Line= 6
 858083.22568578767901.994156423858185.223673589767914.120204772
858244.355447278767919.002021724858246.348855407767919.164268327
858261.895477675767920.714596581858303.529463576767928.179369819
#Sta/Elev= 25
9836.951184.63199838.738183.98479848.808 182.3419858.878182.62469868.949 180.265
9879.019178.4746 9889.09176.3137 9899.16174.56229909.231173.18079919.301170.7419
9929.371167.97119939.442165.44229949.477 163.4079959.511161.93719979.579160.8979
9989.613158.76699999.647 157.76810009.69158.671310016.62161.144210019.78 162.345
10029.94181.4318 10040.1189.997710040.91190.292410050.26192.462610058.92193.9554
#Mann= 3 , 0 , 0
9836.951    0.04       09836.951    0.04       010058.92    0.04       0
#XS Ineff= 2 , 0
       0                               0
Bank Sta=9836.951,10058.92
Exp/Cntr=0.3,0.1

Type RM Length L Ch R = 1 ,17274.46,246.248100,246.248100,246.248100
XS GIS Cut Line= 6
858028.899452521768119.170943581858153.731102337768149.735852575
858182.733521605768155.799700076858240.508549866 768169.28382511
858285.804255848768175.802100823858303.136062784768176.470084811
#Sta/Elev= 28
9842.851197.36259849.132195.26399859.427192.02749869.723189.60559880.018184.7577
9890.314183.94239900.609182.83119910.904181.4506  9921.2179.48799931.495176.8349
9952.086170.07569962.381165.65029972.666 160.4819982.881156.26139993.095  153.46
9997.195 153.51110003.33153.7735 10013.6154.737910034.13156.937810041.48161.5947
 10044.4163.686410064.87 172.21610074.97175.133510085.07178.595110095.17182.7785
10105.28185.568510115.29187.709410123.43189.3292
#Mann= 3 , 0 , 0
9842.851  0.0895       09842.851  0.0895       010123.43  0.0895       0
#XS Ineff= 2 , 0
       0                               0
Bank Sta=9842.851,10123.43
Exp/Cntr=0.3,0.1

Type RM Length L Ch R = 1 ,17028.21,246.248100,246.248100,246.248100
XS GIS Cut Line= 6
858129.245779254768414.124907456858203.935801721768382.924416747
858239.269783459768373.237843313858335.049732703768355.905790724
858365.890391443768345.389754989858384.097843611768336.449244183
#Sta/Elev= 30
9856.201217.90069862.573217.09149873.648213.67159877.435211.35269884.723206.2697
9895.517 199.8029903.408198.39199906.224 198.0269916.931191.50169927.638185.3948
9938.308177.85299948.677169.65249969.415149.23829973.843147.33269979.646145.2404
9989.773145.57659999.906  147.0810010.03146.688510020.14145.928210030.26149.7504
10040.42156.146510050.67158.477610060.93162.982310071.18 169.13510074.04170.1531
10081.74171.945610092.31174.790210102.88179.221110113.96184.3146 10124.1184.8626
#Mann= 3 , 0 , 0
9856.201  0.0686       09856.201  0.0686       0 10124.1  0.0686       0
#XS Ineff= 2 , 0
       0                               0
Bank Sta=9856.201,10124.1
Exp/Cntr=0.3,0.1

Type RM Length L Ch R = 1 ,16781.97,246.248100,246.248100,246.248100
XS GIS Cut Line= 6
858327.480527641768680.889868306858367.737530576768545.392433361
858384.015764888768452.497425867858391.707484652768431.817141878
858403.800743608768408.011879365858432.744825443 768363.25559083
#Sta/Elev= 30
 9870.31199.39739876.453197.44079886.876192.83039896.948187.7093 9907.72179.0966
9928.564168.95089938.986165.48619949.408160.22689959.831154.58659967.939 149.851
9980.675 141.9369991.097138.610910001.57139.112710012.07139.1267 10022.3141.3131
10042.61 143.47810054.27147.678110072.89155.142710082.98157.4825 10103.5159.9985
10114.08159.634110124.75 160.46410128.15162.364610135.79165.938810147.01166.8894
10157.13168.374710170.14 171.54910187.16176.515210206.04181.725610208.16182.1205
#Mann= 3 , 0 , 0
 9870.31    0.04       0 9870.31    0.04       010208.16    0.04       0
#XS Ineff= 2 , 0
       0                               0
Bank Sta=9870.31,10208.16
Exp/Cntr=0.3,0.1

Type RM Length L Ch R = 1 ,16535.72,246.248100,246.248100,246.248100
XS GIS Cut Line= 6
858593.575937711768771.745249549858582.461413516768609.354726861
 858582.01211226768554.734207644858586.057792452768504.391556585
858585.930109685 768468.18667745858580.638759561768422.191138597
#Sta/Elev= 30
9792.425186.6056 9809.21173.63059819.233167.29189829.257165.7998 9839.28162.3845
9849.303157.6275 9869.35155.68219879.374155.66259889.397153.8854 9899.42151.4074
9909.444151.04589929.491148.64719939.514146.77059949.537148.09439959.551145.7697
9979.552136.02259989.553133.162310009.55134.326810019.59133.612910029.62140.9228
10059.71157.120510069.72163.814810079.72166.477110089.72168.199110099.74 171.783
 10109.8173.705910119.86177.253410129.93181.683410139.99187.343710142.83188.3403
#Mann= 3 , 0 , 0
9792.425    0.04       09792.425    0.04       010142.83    0.04       0
#XS Ineff= 2 , 0
       0                               0
Bank Sta=9792.425,10142.83
Exp/Cntr=0.3,0.1

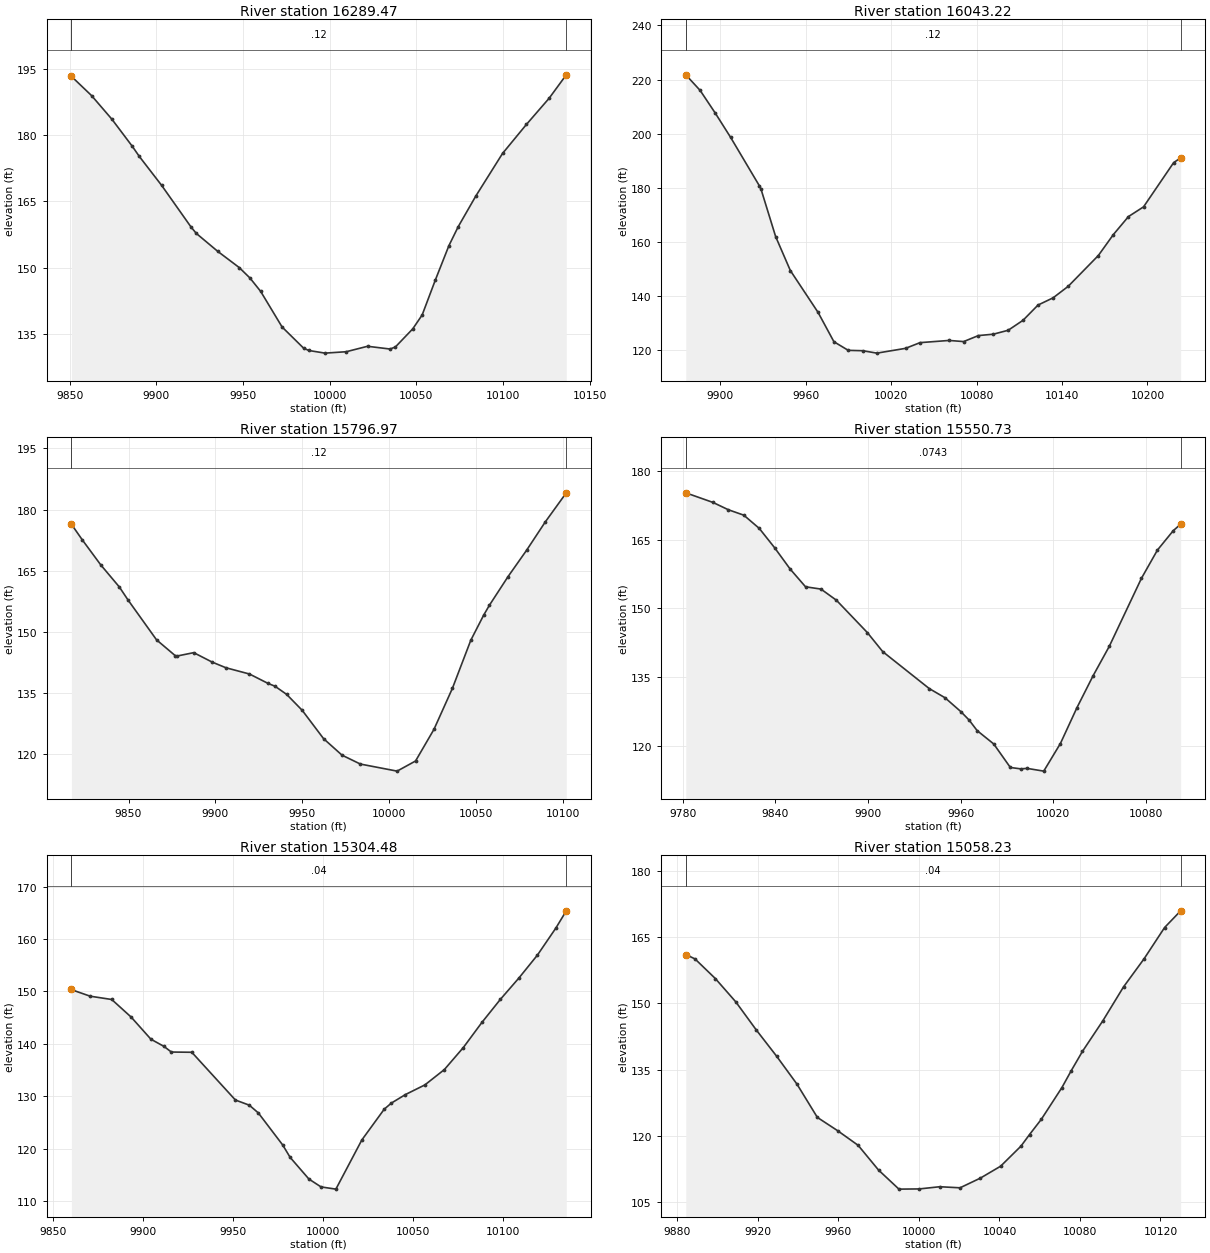
Type RM Length L Ch R = 1 ,16289.47,246.248000,246.248000,246.248000
XS GIS Cut Line= 6
 858863.25328718768544.875778528858842.580661028768511.586150115
858778.477171093768423.609419581858777.379299827768421.937690335
858764.070118934768403.339632147858691.201573565 768317.44881366
#Sta/Elev= 30
 9850.96193.27149862.585188.92149874.356183.55559886.128177.42059890.146175.1458
9903.019168.6002    9920159.16769923.041157.72359935.414153.66239947.787 150.001
9953.962147.6483 9960.16144.60839972.533136.54559984.906131.77049987.924131.2336
9997.279 130.63510009.53130.953110021.83132.184110034.81131.562510037.89132.0252
10047.92 136.13110053.35139.272910061.03 147.261 10068.8154.979210074.15159.2522
10084.26166.159510099.72175.821710113.49182.3833 10126.6188.313510136.51 193.619
#Mann= 3 , 0 , 0
 9850.96    0.12       0 9850.96    0.12       010136.51    0.12       0
#XS Ineff= 2 , 0
       0                               0
Bank Sta=9850.96,10136.51
Exp/Cntr=0.3,0.1

Type RM Length L Ch R = 1 ,16043.22,246.248100,246.248100,246.248100
XS GIS Cut Line= 6
858998.590875975768424.430189982 858980.27760847768376.124223948
858970.289973452768336.065520971858963.192574423768273.599286141
858954.804963467768233.133085595858906.902999546768090.370379167
#Sta/Elev= 30
9875.621221.72779885.706215.97489896.401207.53869907.095198.65629927.282180.7822
 9928.44179.57599938.747162.01829949.097149.45349968.567134.00519979.717123.1565
9989.793119.97639999.865 119.84410009.92118.950610030.03120.714110040.22122.8225
10060.65123.634410070.86123.214610081.26125.433810091.71125.943410102.16127.3909
10112.61131.079110123.15136.710410133.74139.370310144.33143.616510165.52154.9943
10176.11  162.75 10186.7169.386610197.29 172.96810218.47189.325210223.38191.0444
#Mann= 3 , 0 , 0
9875.621    0.12       09875.621    0.12       010223.38    0.12       0
#XS Ineff= 2 , 0
       0                               0
Bank Sta=9875.621,10223.38
Exp/Cntr=0.3,0.1

Type RM Length L Ch R = 1 ,15796.97,246.248100,246.248100,246.248100
XS GIS Cut Line= 6
859236.348857665768350.868830872859235.113242215768346.983624271
859189.437678438768226.619404116859172.865784949768178.352078969
859158.120489881768136.291363084859137.962823256768083.698746245
#Sta/Elev= 30
 9817.15176.39839823.348172.61119834.044166.4368 9844.74161.02239849.732157.8394
9866.132148.07829876.828144.22569877.917144.10829887.523144.93819898.219142.6081
9906.103141.23259919.611139.70489930.307137.40049934.288136.71319941.002134.7096
9949.966130.79929962.256123.85839972.834119.82989983.411117.644210004.55115.9131
10015.15 118.39310025.75126.146510036.34136.172110046.95147.985210054.29154.0803
10057.66156.561210068.37163.566810079.08170.046310089.79176.963210101.89184.0958
#Mann= 3 , 0 , 0
 9817.15    0.12       0 9817.15    0.12       010101.89    0.12       0
#XS Ineff= 2 , 0
       0                               0
Bank Sta=9817.15,10101.89
Exp/Cntr=0.3,0.1

Type RM Length L Ch R = 1 ,15550.73,246.248100,246.248100,246.248100
XS GIS Cut Line= 6
859409.271688991768292.577984429859410.257220065768213.891826695
859405.648974905768129.701091831 859400.77165753 768109.85680668
859375.375496629768046.860418793859356.739373133767980.310596407
#Sta/Elev= 30
    9782175.2288 9799.58173.1383 9809.58171.53799819.581170.35559829.582167.4775
9839.583163.23529849.583158.61449859.584154.72939869.587154.23079879.591151.7984
9899.598144.75339909.601140.58399939.752132.52439949.932130.5299 9960.23127.4936
9965.526125.67199970.751123.3612 9981.51 120.4459992.269115.3175    9999115.0152
10003.12115.1194 10013.9114.521410024.68120.5351 10035.4128.354310045.86135.3208
10056.32141.716310077.23156.603810087.56162.743410097.81166.975310102.61 168.393
#Mann= 3 , 0 , 0
    9782  0.0743       0    9782  0.0743       010102.61  0.0743       0
#XS Ineff= 2 , 0
       0                               0
Bank Sta=9782,10102.61
Exp/Cntr=0.3,0.1

Type RM Length L Ch R = 1 ,15304.48,246.248100,246.248100,246.248100
XS GIS Cut Line= 6
859515.319673553768306.062905779859543.965778952768242.032872301
859560.500394749768218.702566118859616.993957531768159.139091739
859628.901121482 768130.29495309859643.148981869768069.254763525
#Sta/Elev= 30
9860.184150.54069861.297150.20599870.635149.0897 9882.61148.46129893.415145.0991
 9904.39140.88249911.659139.5078 9915.76138.43079927.129138.38699951.379129.2718
9959.098128.28899964.117126.81049977.672120.68969981.817118.32159992.258114.1849
    9999112.683110007.25112.261910021.69121.651810034.16127.534210038.13 128.693
10045.94130.318210056.76132.159910067.58135.088410078.12139.290510088.42144.0705
10098.71148.484910109.01152.558210119.31156.934310129.54162.081810135.37165.3875
#Mann= 3 , 0 , 0
9860.184    0.04       09860.184    0.04       010135.37    0.04       0
#XS Ineff= 2 , 0
       0                               0
Bank Sta=9860.184,10135.37
Exp/Cntr=0.3,0.1

Type RM Length L Ch R = 1 ,15058.23,246.248100,246.248100,246.248100
XS GIS Cut Line= 6
 859815.33386245768329.513193716 859796.73087576768216.157707816
859796.276406958768214.210027645859795.802821524768211.700011078
859789.160194562768160.759277614859774.109089966 768087.18331201
#Sta/Elev= 28
9884.128161.06039888.702160.06389898.836155.60889908.969150.34119919.103144.0066
9929.237138.04869939.371131.71199949.504124.17479959.638121.14629969.772 117.852
9979.906112.25269990.039107.932710000.19107.979410010.31108.4751 10020.4108.2328
10030.48110.420610040.57113.124810050.65117.655610054.93120.2917 10060.8123.7527
10071.01130.921310075.68134.775310081.22139.121310091.43146.103310101.63153.7228
10111.84160.088510122.05167.174710130.03170.9526
#Mann= 3 , 0 , 0
9884.128    0.04       09884.128    0.04       010130.03    0.04       0
#XS Ineff= 2 , 0
       0                               0
Bank Sta=9884.128,10130.03
Exp/Cntr=0.3,0.1