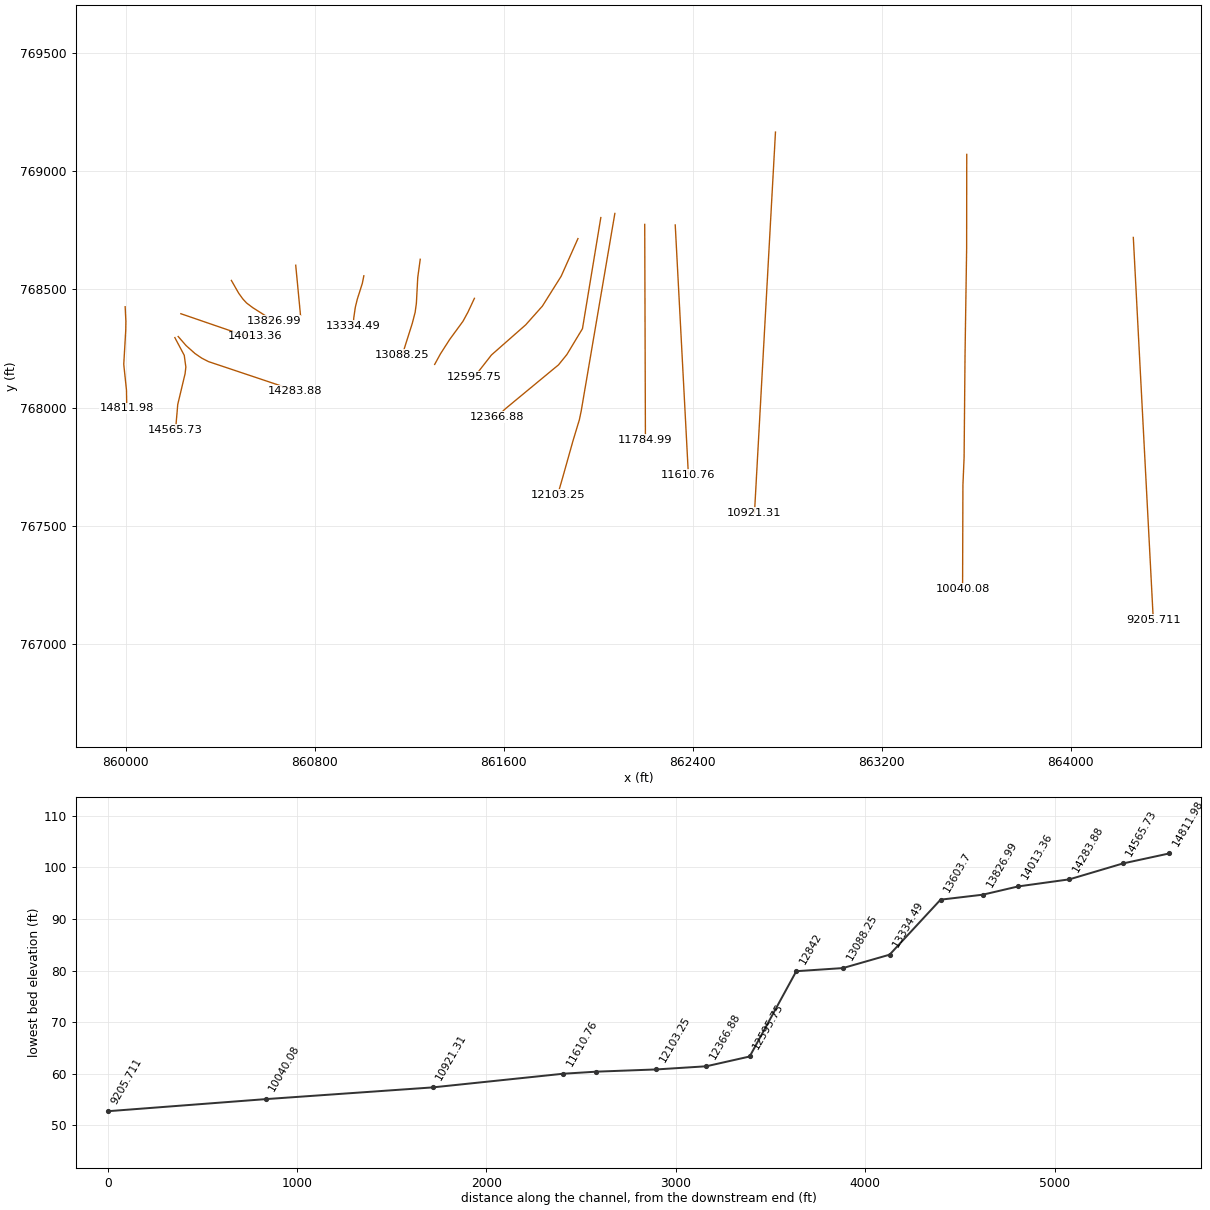
HEC-RAS study 9783_ras.prj: 9783

--- 9783_ras.g01 (geometry) --- (continued)

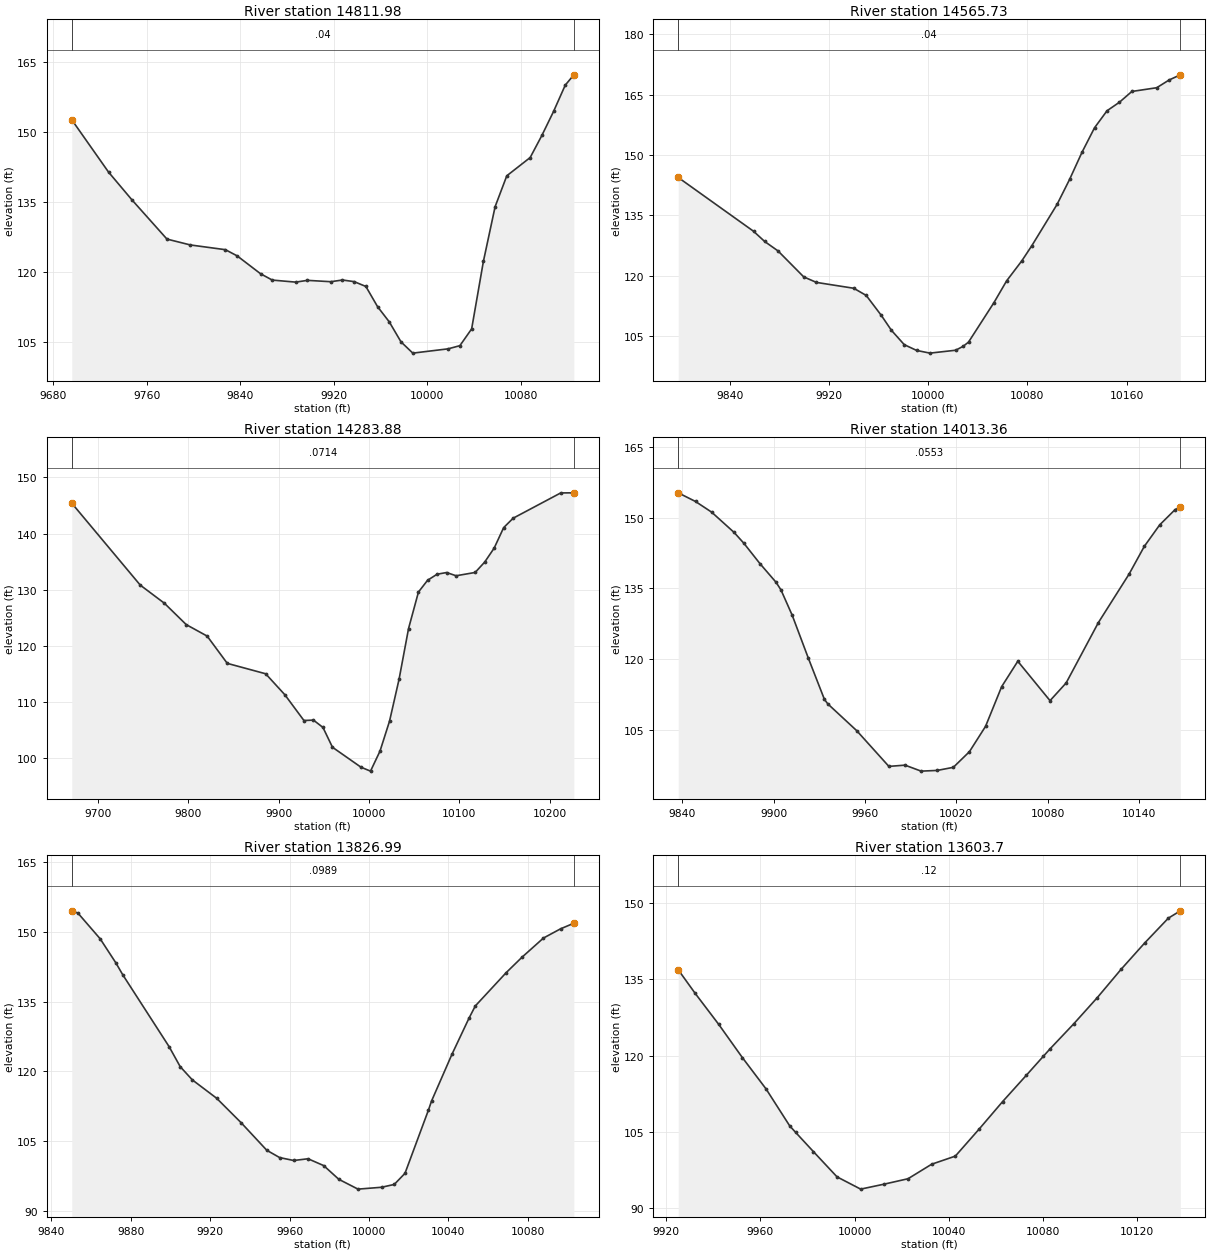
Type RM Length L Ch R = 1 ,14811.98,246.248100,246.248100,246.248100
XS GIS Cut Line= 6
859998.562327325768426.391620114860001.565519811768366.013919548
860001.006331425768326.502082765859992.602291947768182.734231421
860004.126097275768073.388269088860005.375075552767997.635745063
#Sta/Elev= 30
9695.647152.60039727.121141.41149747.132135.47759777.139127.07919797.145125.8253
9827.218124.80969837.242123.4877 9857.29119.66049867.315118.31079887.363 117.874
9897.387118.25149917.406117.9641 9927.41118.32579937.413117.97879947.429116.9453
9957.449112.61839967.469109.36689977.514105.09199987.601102.684910017.84103.6037
10027.91104.281810037.98107.868510048.05122.325810058.07134.013910068.07140.6201
10088.08144.522510098.09149.245710108.09154.3763 10118.1160.006710125.47162.2182
#Mann= 3 , 0 , 0
9695.647    0.04       09695.647    0.04       010125.47    0.04       0
#XS Ineff= 2 , 0
       0                               0
Bank Sta=9695.647,10125.47
Exp/Cntr=0.3,0.1

Type RM Length L Ch R = 1 ,14565.73,281.858800,281.858800,281.858800
XS GIS Cut Line= 6
860208.865742389768295.787756672860248.616330838768220.785706679
860255.356576771768171.150748262860252.089143076768142.936650838
860221.044784269768012.759538945 860211.83522298767905.998296895
#Sta/Elev= 30
9798.444144.41499859.223131.02879868.125128.50569878.935126.14499899.641119.6929
9909.872118.31989939.976116.86499950.043115.07619962.187110.12249970.382106.3981
9980.707102.83559990.645101.4056 10001.4100.730110022.16101.449610028.27102.4396
10032.53103.469810053.06113.303110063.25 118.70410075.45123.657710083.63127.4744
10103.92137.7078   10114143.915410124.07 150.70410134.15156.780210144.23161.0133
10154.25 163.13710164.26165.811910184.29166.740610194.31168.668610203.32169.9491
#Mann= 3 , 0 , 0
9798.444    0.04       09798.444    0.04       010203.32    0.04       0
#XS Ineff= 2 , 0
       0                               0
Bank Sta=9798.444,10203.32
Exp/Cntr=0.3,0.1

Type RM Length L Ch R = 1 ,14283.88,270.510600,270.510600,270.510600
XS GIS Cut Line= 6
 860222.96861122768300.393502446860256.564892778768261.909914347
860294.162886032768228.397385713860322.642471096768208.933935079
860351.390675426 768194.20008584860718.788857203768071.254616698
#Sta/Elev= 30
9671.164145.41099746.974130.81049773.658127.58539797.883123.77199821.025121.7255
9843.278116.86689885.772115.0115 9907.02111.2724 9928.14106.68139938.667106.7548
9949.194105.44729959.722101.91679991.30398.3600210001.8397.6618910012.36101.2406
10022.88106.567710033.41114.018610043.94123.075310054.89129.576910064.99131.6725
10075.52132.752910086.05133.051910096.57132.477210117.63 133.06610128.16134.9063
10138.68137.403110149.21141.057510159.74142.737810212.37147.239210226.89147.2571
#Mann= 3 , 0 , 0
9671.164  0.0714       09671.164  0.0714       010226.89  0.0714       0
#XS Ineff= 2 , 0
       0                               0
Bank Sta=9671.164,10226.89
Exp/Cntr=0.3,0.1

Type RM Length L Ch R = 1 ,14013.36,186.374900,186.374900,186.374900
XS GIS Cut Line= 3
860234.272120839768396.923364052860494.971858697768307.308077745
860548.412622011768301.015123736
#Sta/Elev= 30
9837.477155.25739848.821153.42189859.396151.16419874.156146.86079880.544144.5726
9891.118140.25159901.693136.29229904.917134.67439912.267129.31979922.841120.2402
9933.416111.48389935.679110.51989954.564104.87229975.71397.292029986.28797.55672
9996.86296.2890810007.4496.4375910018.0197.0953410028.58100.410510039.16 105.782
10049.73 114.19510060.31119.570110081.46111.221910092.03114.970510113.15 127.739
10133.32138.027910143.39143.941510153.45 148.47410163.52151.698210166.96152.2009
#Mann= 3 , 0 , 0
9837.477  0.0553       09837.477  0.0553       010166.96  0.0553       0
#XS Ineff= 2 , 0
       0                               0
Bank Sta=9837.477,10166.96
Exp/Cntr=0.3,0.1

Type RM Length L Ch R = 1 ,13826.99,223.291800,223.291800,223.291800
XS GIS Cut Line= 6
 860448.05020589768537.734491827860479.059857188768483.534919954
860496.112543355 768459.92668759860512.166500187768442.386576853
860538.773261877768422.287114496860626.851236288768366.550847779
#Sta/Elev= 30
9850.227154.5587  9853.3154.08799864.535 148.544 9872.42143.38239875.908140.8123
9899.299125.32619904.878121.03179910.994 118.1889923.236 114.2399935.572108.9792
9948.509103.04819954.994101.47539962.065100.84979969.289101.2216 9977.1899.75248
9984.799 96.80379994.47294.6896510006.3495.0898610012.7495.6986610018.1598.09363
10029.96111.683810031.54113.654410041.77123.653810050.34131.405610053.58134.0925
10069.13141.2551 10077.2144.611110087.93148.704510096.53150.683310103.24151.8911
#Mann= 3 , 0 , 0
9850.227  0.0989       09850.227  0.0989       010103.24  0.0989       0
#XS Ineff= 2 , 0
       0                               0
Bank Sta=9850.227,10103.24
Exp/Cntr=0.3,0.1

Type RM Length L Ch R = 1 , 13603.7,269.204400,269.204400,269.204400
XS GIS Cut Line= 2
860720.257779465768602.094884561860740.538267945768389.938541505
#Sta/Elev= 25
9925.136136.86149932.263132.26579942.309126.13329952.354119.5965  9962.4113.4392
9972.446  106.179974.971104.88459982.491 101.1149992.53796.1365910002.5893.72336
10012.6394.7112310022.6795.7655810032.7298.6230710042.76100.215810052.81105.5036
10062.86110.9547 10072.9116.114910080.06119.820210082.95121.303510092.99126.2152
10103.04131.399310113.08136.933810123.13142.132110133.17147.013310138.26148.4586
#Mann= 3 , 0 , 0
9925.136    0.12       09925.136    0.12       010138.26    0.12       0
#XS Ineff= 2 , 0
       0                               0
Bank Sta=9925.136,10138.26
Exp/Cntr=0.3,0.1

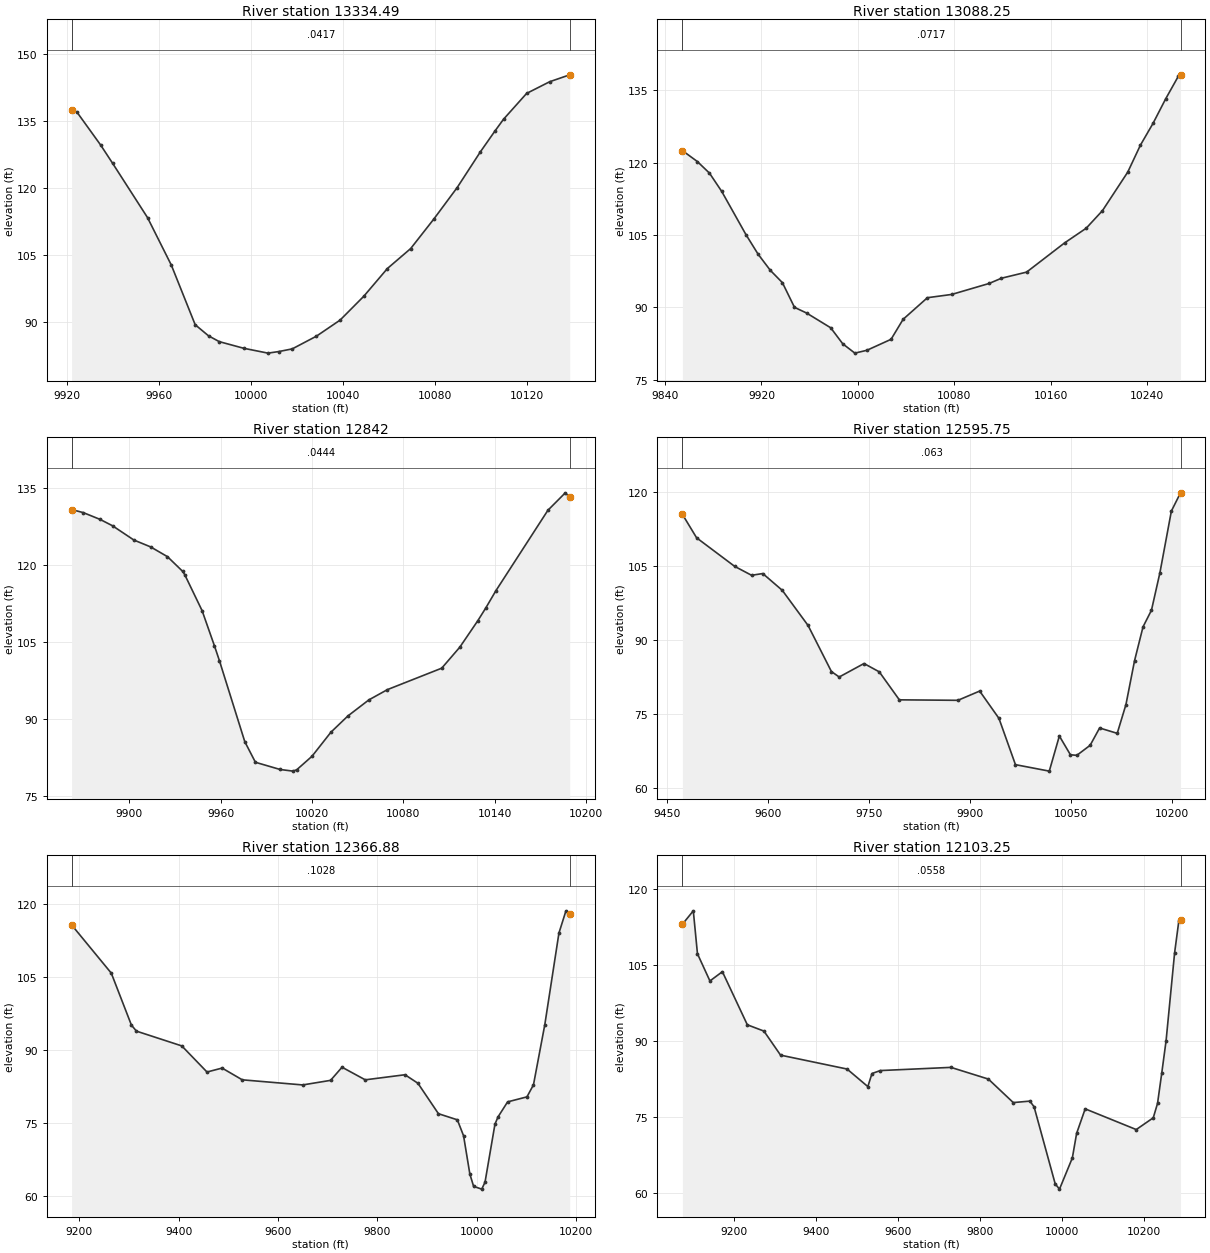
Type RM Length L Ch R = 1 ,13334.49,246.248000,246.248000,246.248000
XS GIS Cut Line= 6
861008.496471991768557.374367554861002.146864559768525.557948443
860980.471515245768457.271257552860972.398201384768424.080898345
860965.783211841768378.796317049860963.735273127768346.302810583
#Sta/Elev= 26
9922.033137.59119924.454136.94959934.651129.66249939.898 125.5429955.055113.4045
9965.422102.76029975.78889.423479981.59686.93528 9986.2585.640579996.84684.15875
10007.4383.0661910012.0883.41342   1001884.01645 10028.586.8579710038.7990.45429
10049.0895.7814210059.37102.007110069.49106.4706 10079.6113.103610089.71120.1208
10099.81128.124610106.08132.738510109.89135.430110119.91 141.19610129.93 143.811
10138.64145.3577
#Mann= 3 , 0 , 0
9922.033  0.0417       09922.033  0.0417       010138.64  0.0417       0
#XS Ineff= 2 , 0
       0                               0
Bank Sta=9922.033,10138.64
Exp/Cntr=0.3,0.1

Type RM Length L Ch R = 1 ,13088.25,246.248100,246.248100,246.248100
XS GIS Cut Line= 6
861247.150641469768627.270033969861236.670288428768550.706192044
861230.807031841768440.997036487861225.579739963768402.928745414
861213.509304607768356.268252165861171.347988489768223.262918012
#Sta/Elev= 30
9854.374122.50039866.759120.23879876.852 117.8239886.945114.05699907.132105.0602
9917.225100.99459927.31897.662929937.36895.094389947.38489.977219957.40188.79736
9977.43485.733049987.45182.401179997.467 80.474910007.4881.06722 10027.583.34052
10037.5187.4921210057.6791.9757310077.8692.65565 10108.894.9244510119.1396.02095
10139.9797.2861110171.44103.3392 10189.4106.390410202.91110.043210223.89118.0377
10234.38123.625410244.87128.154310255.36133.242610265.85137.924910267.67138.2262
#Mann= 3 , 0 , 0
9854.374  0.0717       09854.374  0.0717       010267.67  0.0717       0
#XS Ineff= 2 , 0
       0                               0
Bank Sta=9854.374,10267.67
Exp/Cntr=0.3,0.1

Type RM Length L Ch R = 1 ,   12842,246.248100,246.248100,246.248100
XS GIS Cut Line= 6
861476.411546402768462.035175144861448.741259136 768403.01935698
 861427.61161753768364.335174427861372.294889329768288.853670717
861332.821497385768227.354316819861308.212671903768182.463076014
#Sta/Elev= 30
9862.066130.76829869.836130.1584 9880.88128.83449888.947127.6092 9902.97 124.834
9914.014123.49129925.059121.59149935.051118.72719936.384 118.0949947.778111.0961
9955.912104.22559959.173 101.3469975.81585.601829982.80181.59113    999980.18855
 10007.579.8684910009.9380.1327110019.9482.7539810032.3887.4398910043.5590.60801
10057.2693.7215110069.4995.7285210105.1499.8992610117.02 103.984 10128.9109.1617
10133.95111.551710140.67114.947210174.88130.625110186.29134.016310189.18 133.132
#Mann= 3 , 0 , 0
9862.066  0.0444       09862.066  0.0444       010189.18  0.0444       0
#XS Ineff= 2 , 0
       0                               0
Bank Sta=9862.066,10189.18
Exp/Cntr=0.3,0.1

Type RM Length L Ch R = 1 ,12595.75,228.871100,228.871100,228.871100
XS GIS Cut Line= 6
861914.485488056768714.806694274861843.552226101768555.691668646
861763.950334694   768429.046511861693.598341522768350.036113691
861548.629256772768222.503339696861476.803646119768130.638854459
#Sta/Elev= 30
9473.409115.52959494.545110.75229550.947104.96319576.136103.1417 9592.78103.4942
9621.779 100.0829660.07692.939319694.73183.582439706.28382.470469743.13785.21151
9765.80683.519729795.60577.832159882.58877.734969914.89879.615189943.52674.06468
 9968.0464.6612710018.2863.3460110033.2370.4812610049.6766.6718610059.1866.55435
10078.9368.5919210093.0172.1143510119.1871.0243910132.1376.8748510144.9485.80939
10157.4992.6618310170.0396.0448910182.58103.662910199.59116.189510213.16119.8963
#Mann= 3 , 0 , 0
9473.409   0.063       09473.409   0.063       010213.16   0.063       0
#XS Ineff= 2 , 0
       09872.552                       0
Bank Sta=9473.409,10213.16
Exp/Cntr=0.3,0.1

Type RM Length L Ch R = 1 ,12366.88,263.625100,263.625100,263.625100
XS GIS Cut Line= 6
862011.285136973 768803.84272012861933.590928755768333.628481253
861867.490575941768223.995725429861832.188857952768180.519570763
861604.763760769767992.552625595861572.178826671767959.642558735
#Sta/Elev= 30
9184.484115.77399264.395 105.8519304.93895.162049315.07393.927469406.29490.88953
9456.97285.524599487.37886.335659527.92183.921279649.54882.869729705.63883.81061
9728.71286.512579775.40183.918539855.39484.963519881.40183.215019922.70776.95384
9960.73775.698179973.25772.414529985.89564.558049993.44662.01964 10009.861.45167
10016.4162.8787910036.4274.8113610042.5276.2847310061.8679.38687 10100.880.41643
10113.9282.8969310136.6995.2492710165.17114.098510179.24118.659410186.78118.0041
#Mann= 3 , 0 , 0
9184.484  0.1028       09184.484  0.1028       010186.78  0.1028       0
#XS Ineff= 2 , 0
       09843.005                       0
Bank Sta=9184.484,10186.78
Exp/Cntr=0.3,0.1

Type RM Length L Ch R = 1 ,12103.25,318.260500,318.260500,318.260500
XS GIS Cut Line= 6
862070.640819342768821.258633825861928.429873774767986.382902916
861920.635715037767948.743636988861893.648617076767859.700528521
 861848.61379118767699.418231003861828.767528367767631.149921682
#Sta/Elev= 30
9073.143113.03549099.779115.68659109.923107.22359140.356101.86589170.788103.6918
9231.65293.226679272.228 91.98449312.804 87.24559475.10984.508689525.82981.04889
9535.97383.624179556.26184.20567 9728.7184.835129820.00682.53252 9880.8777.89772
9921.45678.187119931.668 77.05839983.26261.864479993.69960.8413510025.0666.98767
10035.5271.8323110056.4176.6614410181.0572.5802410222.6274.8997310233.0377.73836
10243.4483.7779210253.8690.0585510274.69107.3989 10285.1113.754710289.11113.8661
#Mann= 3 , 0 , 0
9073.143  0.0558       09073.143  0.0558       010289.11  0.0558       0
#XS Ineff= 2 , 0
       09751.886        10123.23       0
Bank Sta=9073.143,10289.11
Exp/Cntr=0.3,0.1

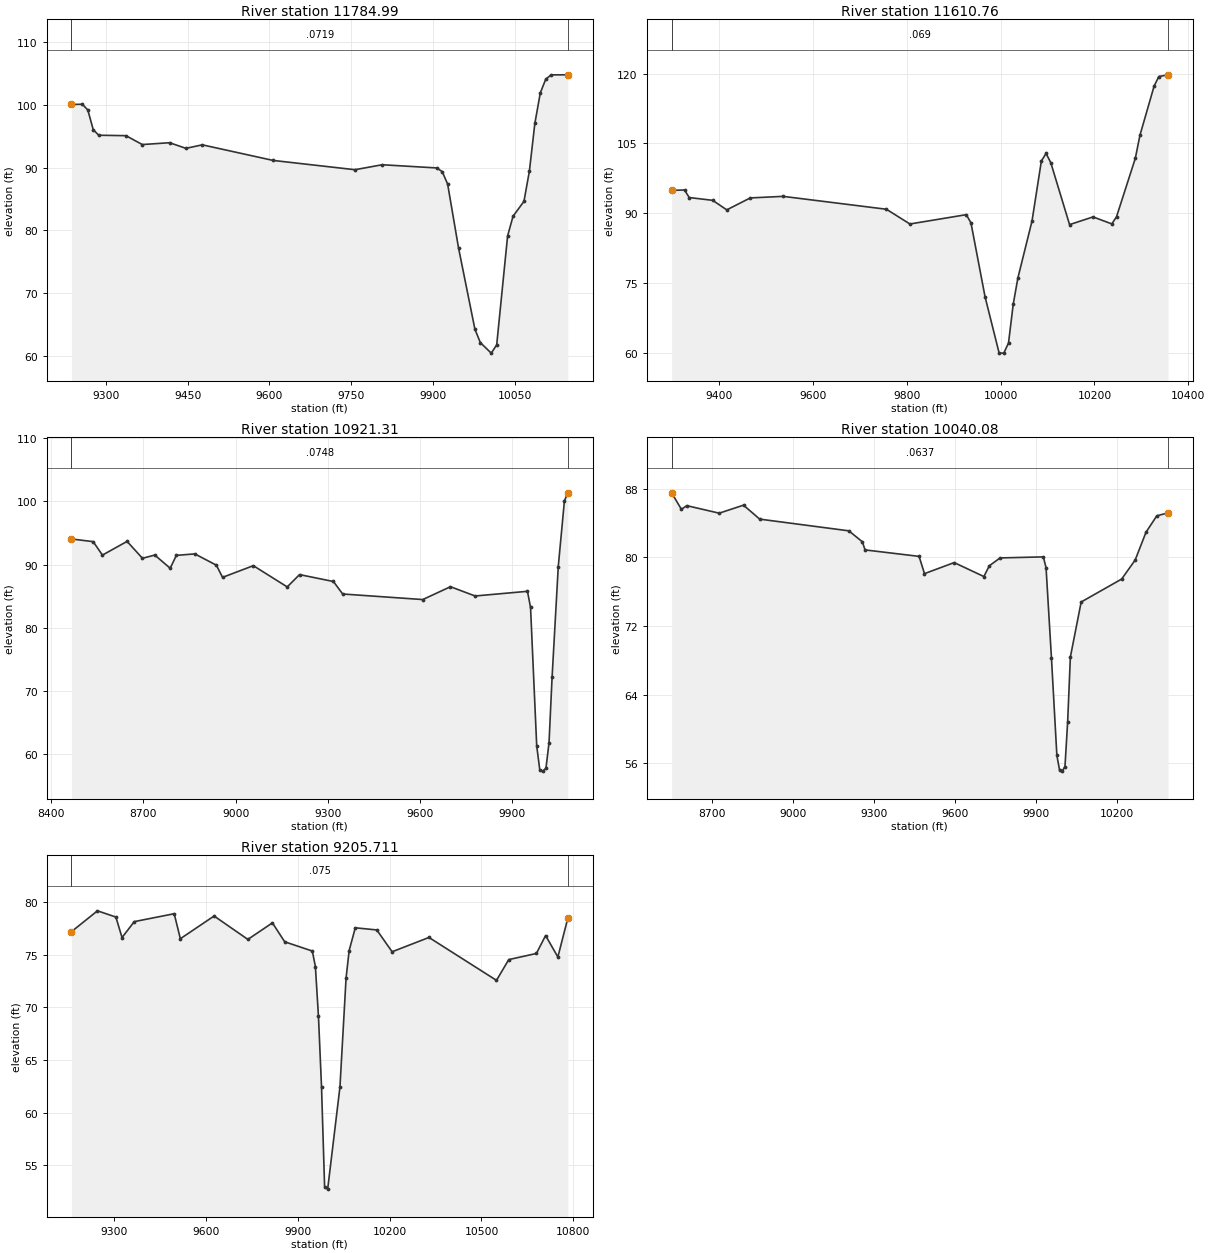
Type RM Length L Ch R = 1 ,11784.99,174.235700,174.235700,174.235700
XS GIS Cut Line= 2
862197.041655916768774.918095268862199.992055616767864.525121352
#Sta/Elev= 30
 9237.03100.09369256.948100.12979266.94899.223299276.94896.073319286.948 95.1835
9336.949 95.11579366.94993.697369416.94993.990839446.94993.091649476.94993.65415
 9606.9591.162529756.95189.681879806.951 90.47499906.952 89.96449916.95289.38609
9926.95287.396449946.95277.195349976.95264.239279986.95262.0821610006.9560.40737
10016.9561.7256810036.9579.1085910046.9582.2609910066.9584.6288510076.95 89.4786
10086.9597.0828310096.95  101.9510106.95104.135510116.95104.821210147.43104.8269
#Mann= 3 , 0 , 0
 9237.03  0.0719       0 9237.03  0.0719       010147.43  0.0719       0
#XS Ineff= 2 , 0
       09871.513                       0
Bank Sta=9237.03,10147.43
Exp/Cntr=0.3,0.1

Type RM Length L Ch R = 1 ,11610.76,689.449000,689.449000,689.449000
XS GIS Cut Line= 2
862326.161622441768772.388934817862381.772940918767715.356443594
#Sta/Elev= 30
9298.416 94.92929325.84395.015659335.85793.392489385.92692.791719415.968 90.7476
9466.03793.309969536.13493.643989756.43890.878319806.50787.714869926.67389.71668
9936.68787.971119966.72872.10348 9996.7760.0235610006.7860.00608 10016.8 62.1943
10026.8170.4919210036.8376.1601710066.8788.3384510086.89101.255210096.91102.8498
10106.92100.872110146.9887.5795310197.0589.23436 10237.187.7309610247.1289.27104
10287.17101.797410297.18106.798310327.23117.288110337.24119.353810356.91119.7234
#Mann= 3 , 0 , 0
9298.416   0.069       09298.416   0.069       010356.91   0.069       0
#XS Ineff= 2 , 0
       0                               0
Bank Sta=9298.416,10356.91
Exp/Cntr=0.3,0.1

Type RM Length L Ch R = 1 ,10921.31,881.224300,881.224300,881.224300
XS GIS Cut Line= 2
862750.285639737769165.476029552862661.451361993767553.939893307
#Sta/Elev= 30
8465.96594.065218536.548 93.64088566.59391.513228646.71593.682148696.79191.00967
8736.85191.521278786.92789.437428806.95891.471948867.04991.703568937.15589.91925
8957.18587.995049057.33789.843189167.50486.483789207.56588.430699317.73287.34084
9347.777 85.36519608.17284.485169698.30986.51583 9778.4385.050999948.68885.79026
9958.70383.233699978.73461.365699988.74957.558159998.76457.3593110008.7857.80703
10018.7961.8477810028.8172.2732610048.84 89.709510068.87 100.10210079.95101.3605
#Mann= 3 , 0 , 0
8465.965  0.0748       08465.965  0.0748       010079.95  0.0748       0
#XS Ineff= 2 , 0
       0                               0
Bank Sta=8465.965,10079.95
Exp/Cntr=0.3,0.1

Type RM Length L Ch R = 1 ,10040.08,834.372600,834.372600,834.372600
XS GIS Cut Line= 6
863559.633090066769071.006215163863559.169529679768673.385137511
863552.456720709768226.751897211863548.422658623767788.965604255
863543.450153464767671.110469127863542.005401306767233.512789967
#Sta/Elev= 30
8551.04687.505248587.052 85.58568607.05286.011548727.05285.134528817.05286.06712
8877.05284.441769207.08183.078419257.08781.802139267.08880.856549467.106 80.1028
9487.10778.091969597.11179.379679707.11677.753369727.117 79.00869767.11879.92337
9927.20580.044259937.21478.779789957.22668.256469977.226 56.92599987.22655.20178
9997.22655.0892810007.2355.6212710017.2360.8680210027.2368.3824810067.2374.79039
10217.2377.4650510267.2379.6838410307.2382.9143610347.2384.8267510388.7285.16925
#Mann= 3 , 0 , 0
8551.046  0.0637       08551.046  0.0637       010388.72  0.0637       0
#XS Ineff= 2 , 0
       0                               0
Bank Sta=8551.046,10388.72
Exp/Cntr=0.3,0.1

Type RM Length L Ch R = 1 ,9205.711,842.652600,842.652600,842.652600
XS GIS Cut Line= 2
864264.439342651768719.654837297864348.950987599 767102.52108607
#Sta/Elev= 30
 9162.3777.18982 9247.1479.164479307.22278.573689327.24976.630539367.30478.14025
9497.48178.889999517.50876.515159627.65878.671789737.80976.451319817.91878.02186
9857.97276.224669948.09575.345869958.10973.877149968.12269.145569978.136 62.4298
 9988.1552.988659998.16352.7435210038.2262.4357410058.2572.7943410068.2675.39244
10088.2977.5533810158.3877.3498310208.4575.2772510328.6176.6365510548.9172.56365
10588.9774.5350810679.0975.1151710709.1376.8176110749.1974.7806910781.7178.47745
#Mann= 3 , 0 , 0
 9162.37   0.075       0 9162.37   0.075       010781.71   0.075       0
#XS Ineff= 2 , 0
       0                               0
Bank Sta=9162.37,10781.71
Exp/Cntr=0.3,0.1