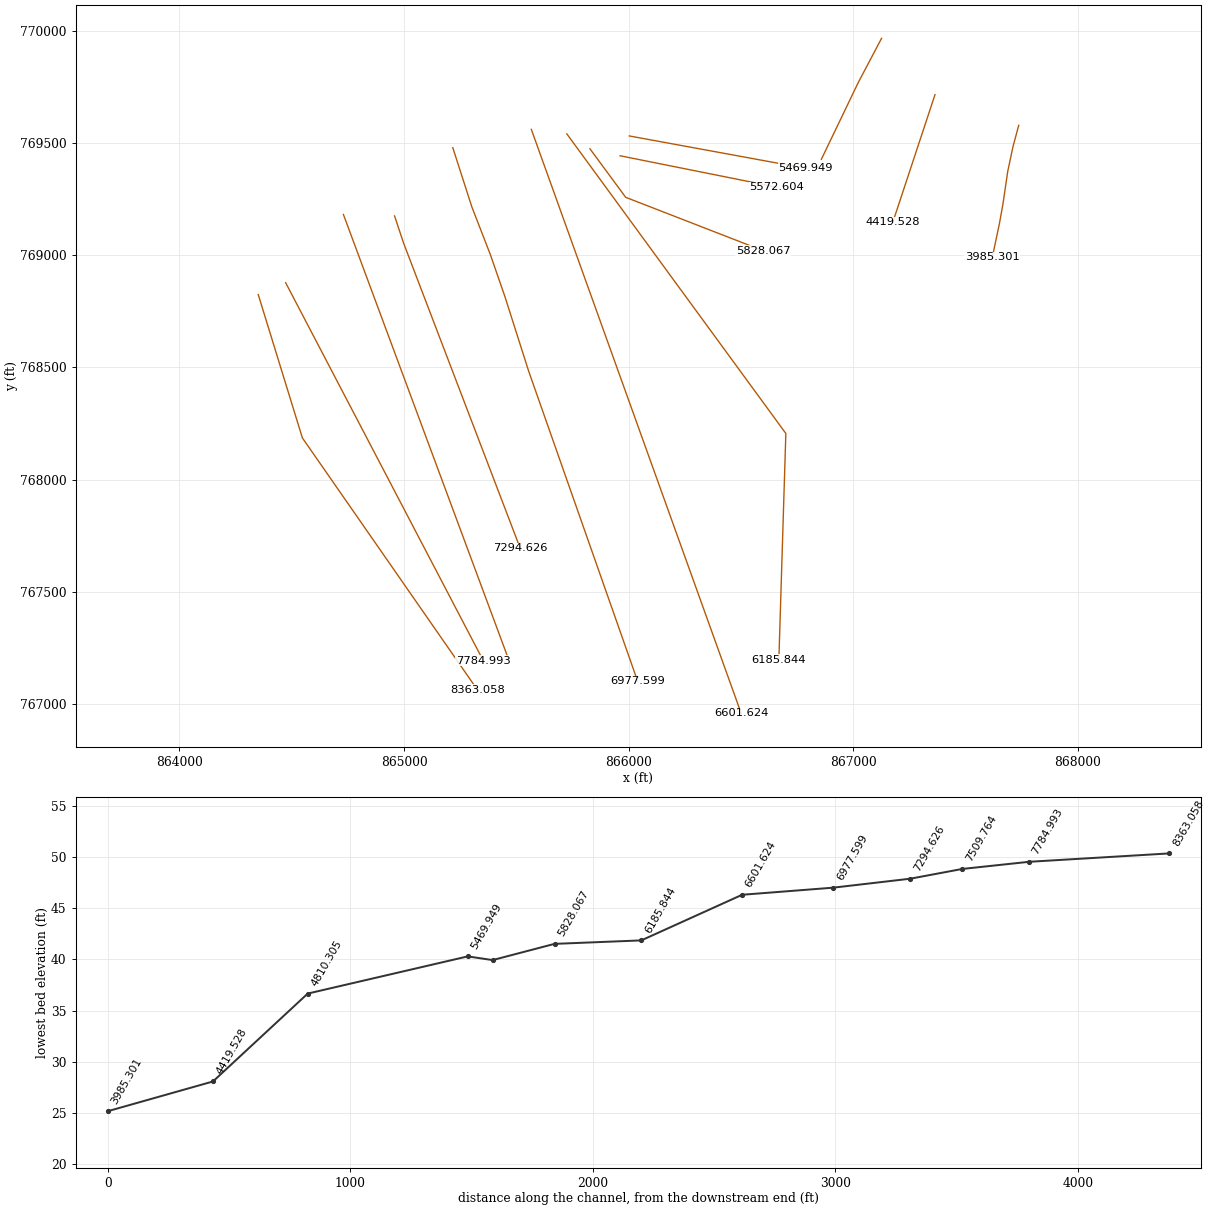
HEC-RAS study 9783_ras.prj: 9783

--- 9783_ras.g01 (geometry) --- (continued)

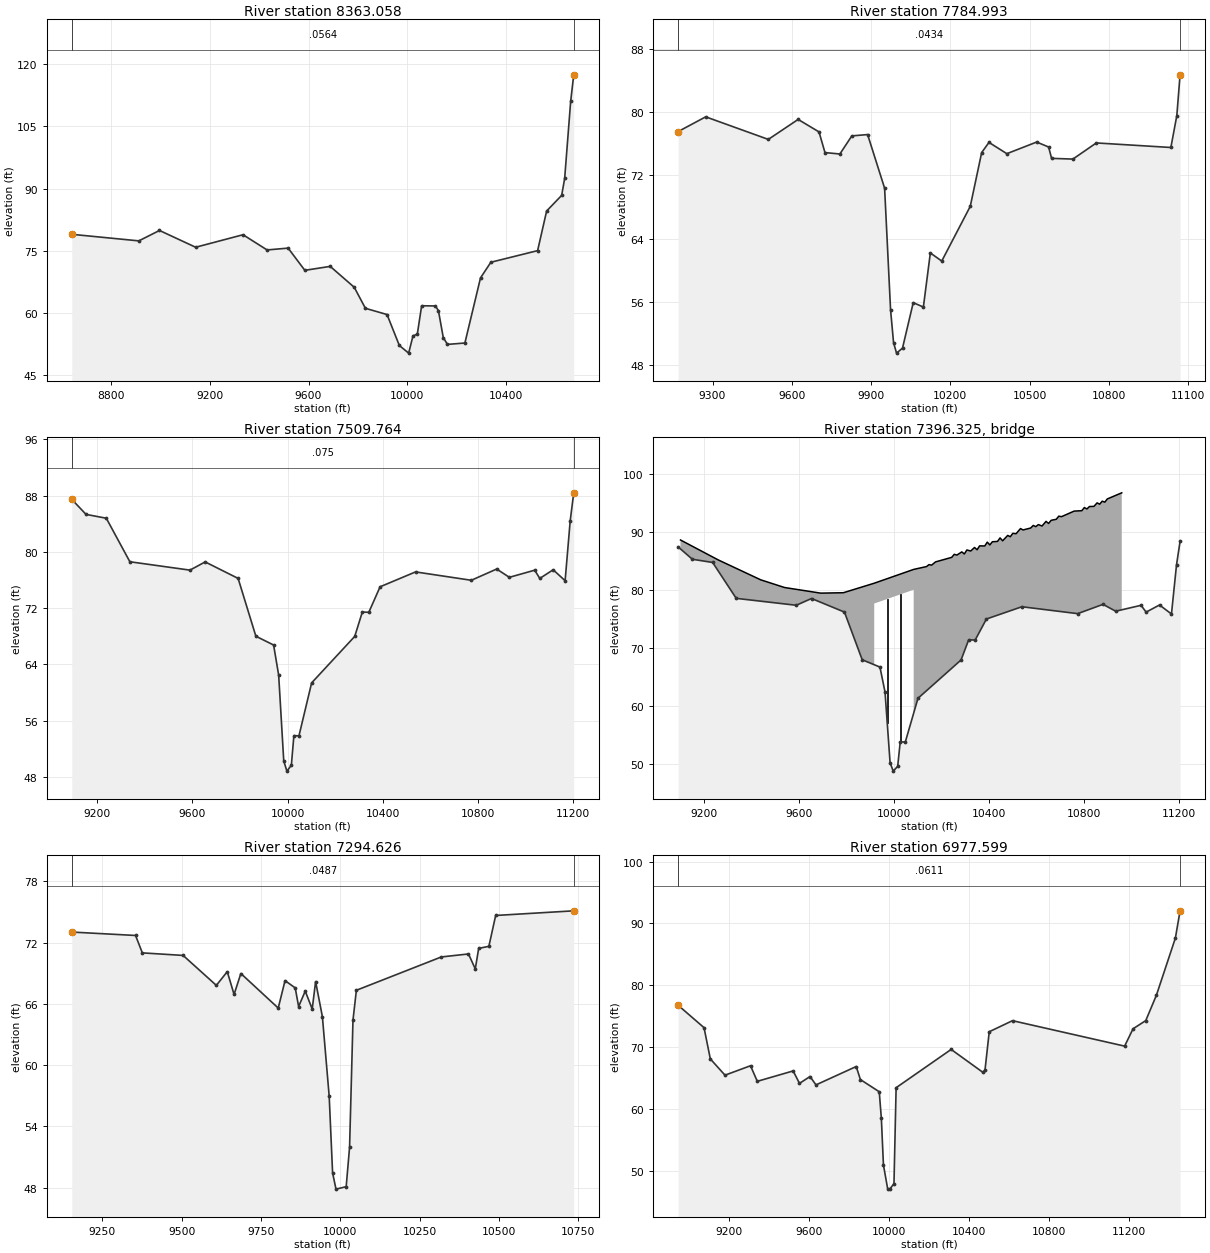
Type RM Length L Ch R = 1 ,8363.058,578.065100,578.065100,578.065100
XS GIS Cut Line= 3
864350.738293399768824.646627315 864547.26187299768186.370399942
865326.595241463767064.856735299
#Sta/Elev= 30
8640.867 78.96718912.54377.384358996.24979.894229142.73575.848159334.73778.86284
9432.15575.197719517.39775.640569585.134 70.2852 9687.8871.239479785.29866.19805
 9830.4761.13723 9918.09 59.63029967.95952.1748910005.7150.3334410023.2354.49165
10040.7654.9036710058.2861.7462110114.0961.7056710126.2660.57288 10145.954.09553
 10162.852.4367610233.5252.7710210296.7568.4588210338.6772.2316410528.1275.03014
10564.6584.5808210625.5488.3480310637.7192.4267410662.07111.037310674.42117.3982
#Mann= 3 , 0 , 0
8640.867  0.0564       08640.867  0.0564       010674.42  0.0564       0
#XS Ineff= 2 , 0
       0                10094.83       0
Bank Sta=8640.867,10674.42
Exp/Cntr=0.3,0.1

Type RM Length L Ch R = 1 ,7784.993,275.228900,275.228900,275.228900
XS GIS Cut Line= 2
864472.689831537768877.537352568865352.906084992767194.124470559
#Sta/Elev= 30
9169.78677.55538 9274.21 79.42319511.18476.566479624.02979.094629703.02177.51485
 9725.5974.898239782.01274.71925 9827.1577.010099886.96577.17853 9951.2870.38914
9973.84954.983699985.13350.846239996.418  49.51510018.9950.1440710059.6255.90475
10097.9855.3474210124.3662.1937110167.5361.1686710275.4368.09261 10318.674.90045
10346.2476.1847610413.9474.7597510526.7976.2319110571.9375.6045810583.2174.16586
 10663.974.0760310752.4876.1192511034.5975.5428911057.1679.5812811069.4384.73997
#Mann= 3 , 0 , 0
9169.786  0.0434       09169.786  0.0434       011069.43  0.0434       0
#XS Ineff= 2 , 0
       0                10366.87       0
Bank Sta=9169.786,11069.43
Exp/Cntr=0.3,0.1

Type RM Length L Ch R = 1 ,7509.764,215.138800,215.138800,215.138800
XS GIS Cut Line= 2
864729.888191992769181.270728872865465.108983271767201.055333497
#Sta/Elev= 30
9092.05287.473639152.07685.335119237.41284.786379336.579 78.59739589.42477.40609
9653.42678.574599792.097 76.22949866.76668.007469941.43566.754349962.76962.46174
9984.10350.261129997.37248.81876 10016.149.6504210026.7753.8625410048.1153.83527
10101.4461.3704610282.78 67.979410314.78  71.44710342.1371.4111510389.4575.03612
10538.7977.1534110773.4675.9624210880.1377.5623710933.47 76.382811040.1477.39985
11061.47 76.226511117.8577.4574711168.1475.9018211189.4884.4066311204.3588.40085
#Mann= 3 , 0 , 0
9092.052   0.075       09092.052   0.075       011204.35   0.075       0
#XS Ineff= 2 , 0
       09896.544        10105.54       0
Bank Sta=9092.052,11204.35
Exp/Cntr=0.3,0.1

Type RM Length L Ch R = 3 ,7396.325,,,
BEGIN DESCRIPTION:
END DESCRIPTION:
Bridge Culvert--1,0,-1,-1, 0
Deck Dist Width WeirC Skew NumUp NumDn MinLoCord MaxHiCord MaxSubmerge Is_Ogee
57.069400,101.000000,2.6,0, 60, 60, , , 0.95, 0, 0,0,,
 9102.12 9260.69 9439.35 9539.84 9691.95 9787.41 9917.36 9917.3610083.3610083.36
10137.4110148.0210158.6310175.1110243.4710254.0810265.1410285.9010296.5110307.15
10323.2610339.3910350.1410360.8910382.3810393.1310403.8810414.6310436.1210446.87
10457.6210479.1210489.8610500.6110514.2610532.8510543.6010575.8510586.5910597.34
10608.0910623.4010640.3310651.0810661.8310683.3210694.0710705.2510758.5610790.80
10801.5510812.3010823.0510841.6810855.2910866.0410876.7910887.5310898.2810958.93
   88.66   85.23   81.80   80.47   79.50   79.57   81.21   81.21   83.59   83.59
   84.08   84.42   84.32   84.88   85.67   86.19   86.06   86.61   86.25   86.94
   86.76   87.37   86.98   87.65   87.63   88.29   87.81   88.36   88.41   89.02
   88.52   89.45   89.22   89.81   89.74   90.63   90.39   90.73   91.17   90.96
   91.32   91.07   91.87   91.51   92.05   92.23   92.77   92.68   93.64   93.71
   94.25   94.01   94.43   94.45   95.06   94.83   95.35   95.18   95.74   96.79
 -911.34 -914.77 -918.20 -919.53 -920.50 -920.43 -918.79   77.71   80.09 -916.41
 -915.92 -915.58 -915.68 -915.12 -914.33 -913.81 -913.94 -913.39 -913.75 -913.06
 -913.24 -912.63 -913.02 -912.35 -912.37 -911.71 -912.19 -911.64 -911.59 -910.98
 -911.48 -910.55 -910.78 -910.19 -910.26 -909.37 -909.61 -909.27 -908.83 -909.04
 -908.68 -908.93 -908.13 -908.49 -907.95 -907.77 -907.23 -907.32 -906.36 -906.29
 -905.75 -905.99 -905.57 -905.55 -904.94 -905.17 -904.65 -904.82 -904.26 -903.21
 9102.12 9260.69 9439.35 9539.84 9691.95 9787.41 9911.83 9911.8310077.8310077.83
10137.4110148.0210158.6310175.1110243.4710254.0810265.1410285.9010296.5110307.15
10323.2610339.3910350.1410360.8910382.3810393.1310403.8810414.6310436.1210446.87
10457.6210479.1210489.8610500.6110514.2610532.8510543.6010575.8510586.5910597.34
10608.0910623.4010640.3310651.0810661.8310683.3210694.0710705.2510758.5610790.80
10801.5510812.3010823.0510841.6810855.2910866.0410876.7910887.5310898.2810958.93
   88.66   85.23   81.80   80.47   79.50   79.57   81.13   81.13   83.51   83.51
   84.08   84.42   84.32   84.88   85.67   86.19   86.06   86.61   86.25   86.94
   86.76   87.37   86.98   87.65   87.63   88.29   87.81   88.36   88.41   89.02
   88.52   89.45   89.22   89.81   89.74   90.63   90.39   90.73   91.17   90.96
   91.32   91.07   91.87   91.51   92.05   92.23   92.77   92.68   93.64   93.71
   94.25   94.01   94.43   94.45   95.06   94.83   95.35   95.18   95.74   96.79
 -911.34 -914.77 -918.20 -919.53 -920.50 -920.43 -918.87   77.63   80.01 -916.49
 -915.92 -915.58 -915.68 -915.12 -914.33 -913.81 -913.94 -913.39 -913.75 -913.06
 -913.24 -912.63 -913.02 -912.35 -912.37 -911.71 -912.19 -911.64 -911.59 -910.98
 -911.48 -910.55 -910.78 -910.19 -910.26 -909.37 -909.61 -909.27 -908.83 -909.04
 -908.68 -908.93 -908.13 -908.49 -907.95 -907.77 -907.23 -907.32 -906.36 -906.29
 -905.75 -905.99 -905.57 -905.55 -904.94 -905.17 -904.65 -904.82 -904.26 -903.21
Pier Skew, UpSta & Num, DnSta & Num=  ,9972.03, 2 ,9966.50, 2 , 0 , 0 , 0 ,,
    4.00    4.00
 -918.01   81.99
    4.00    4.00
 -918.09   81.91
Pier Skew, UpSta & Num, DnSta & Num=  ,10028.69, 2 ,10023.17, 2 , 0 , 0 , 0 ,,
    4.00    4.00
 -917.20   82.80
    4.00    4.00
 -917.28   82.72
BR Coef=-1 , 0 , 0 ,, 0 ,,,0.8,0,1,0,
WSPro=,,,, 1 ,,,, 0 ,,,, 0 ,,,,-1 ,-1 ,-1 , 0 , 0 , 0 , 0 , 0
BC Design=,, 0 ,, 0 ,,,,,,

Type RM Length L Ch R = 1 ,7294.626,317.027000,317.027000,317.027000
XS GIS Cut Line= 3
864957.655034874769174.636816553864997.658484676 769054.20284242
865517.036452916767695.229061697
#Sta/Elev= 30
9153.498 73.04519354.48772.710529375.898  71.0059504.36370.75578 9609.0967.82203
9643.53469.167019664.945 66.93159686.35668.984049804.115 65.59929825.52668.28697
9857.64367.574229868.34865.744279889.20267.26188 9911.17 65.50169921.87568.19349
9943.28664.751399964.69756.948839975.40249.458169986.10847.8638910018.2248.10313
10028.9351.9723210039.6464.4151110050.3467.3412810317.98 70.606310403.6270.89958
10425.0369.4347910435.7471.4452710467.85 71.647110489.2674.6696110735.2475.12444
#Mann= 3 , 0 , 0
9153.498  0.0487       09153.498  0.0487       010735.24  0.0487       0
#XS Ineff= 2 , 0
       09875.391        10115.09       0
Bank Sta=9153.498,10735.24
Exp/Cntr=0.3,0.1

Type RM Length L Ch R = 1 ,6977.599,375.974600,375.974600,375.974600
XS GIS Cut Line= 6
 865216.90692124769478.642417387865301.760430195769214.757246831
865384.047290534769002.757626485865448.636041055768816.564221663
865554.651421954768483.732193016 866040.00741823767102.823274329
#Sta/Elev= 30
8943.46776.754939073.34573.126249104.85868.071769178.38865.434949306.21466.96479
9340.15764.441479519.78866.123389551.54164.108589604.464 65.21739634.05263.86303
9835.69966.836459856.68964.725539951.14562.75273 9961.6458.467179972.13550.90927
9993.12547.0808910003.7346.9913210024.9247.8778410035.64 63.407710311.4269.60585
10470.3765.8950910480.9766.2761610502.1672.4675710618.7374.2582111180.3670.13939
11222.7572.9495111286.3374.2709811339.3178.3490711434.6887.6244811458.1892.03923
#Mann= 3 , 0 , 0
8943.467  0.0611       08943.467  0.0611       011458.18  0.0611       0
#XS Ineff= 2 , 0
       09662.364        10315.38       0
Bank Sta=8943.467,11458.18
Exp/Cntr=0.3,0.1

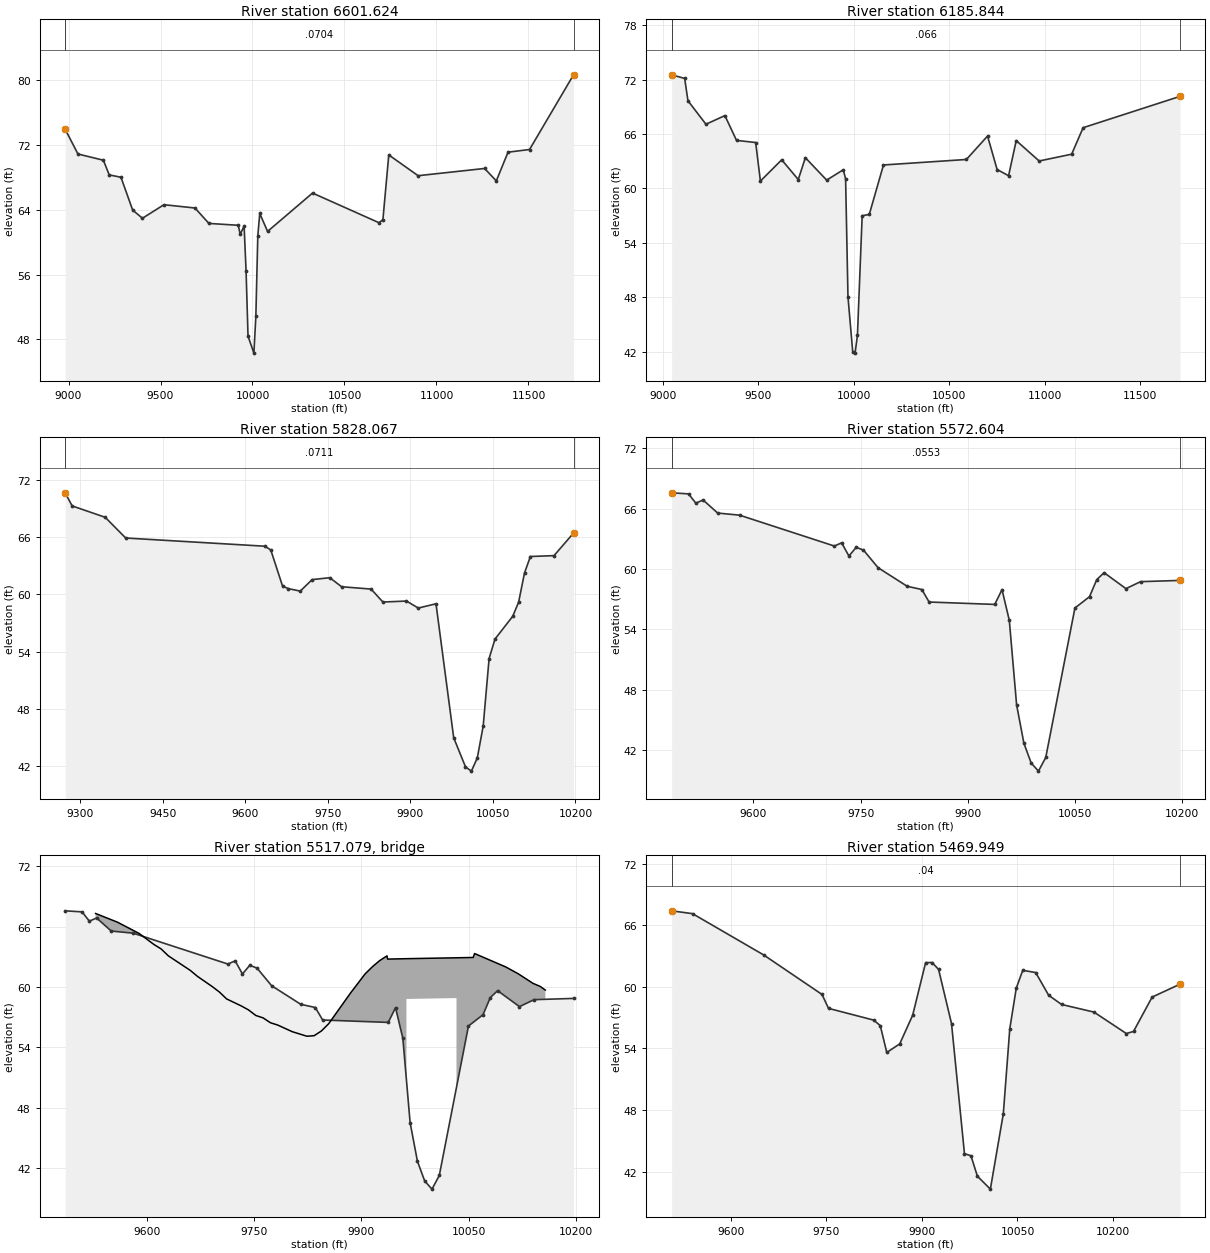
Type RM Length L Ch R = 1 ,6601.624,415.780200,415.780200,415.780200
XS GIS Cut Line= 2
865566.505983541769560.169387908866500.936175014766959.991479377
#Sta/Elev= 30
8982.02673.943559051.27670.892479189.41570.125669221.29468.313469285.05168.01949
9348.80763.961279401.93862.958629518.82664.629039687.22164.223489763.22762.31689
9922.61962.088759933.24560.966919954.49761.994669965.12356.45034 9975.7548.39209
10007.6346.2976110018.2550.8277510028.8860.7802710039.5163.5450710082.0161.32959
10326.4166.06863 10687.762.4035710708.9562.7906910740.8370.7797410900.2268.21199
11261.5169.1054911325.2767.5733311389.0371.1193111505.9171.4473911745.0180.67157
#Mann= 3 , 0 , 0
8982.026  0.0704       08982.026  0.0704       011745.01  0.0704       0
#XS Ineff= 2 , 0
       09459.285        10419.24       0
Bank Sta=8982.026,11745.01
Exp/Cntr=0.3,0.1

Type RM Length L Ch R = 1 ,6185.844,357.776600,357.776600,357.776600
XS GIS Cut Line= 3
865724.728113721769539.913177114866699.723983162768206.207045182
866668.597633742767198.229753499
#Sta/Elev= 30
9047.63472.529259115.65672.131869132.81869.670119227.14167.079639326.23868.03536
9386.98665.301599487.27265.066839512.04660.814469623.53163.160299710.24160.98393
9747.40363.391219858.88760.919249945.59762.059499957.98561.065689970.372 48.0513
9995.146 42.023310007.5341.8452910019.9243.8063110044.69 56.993610081.8657.13683
10156.18 62.589710590.0563.1958310700.9365.7783910750.9562.0888710810.9861.40423
   1085165.2786610971.0663.0286611141.1463.7801311201.17 66.700211708.1870.15333
#Mann= 3 , 0 , 0
9047.634   0.066       09047.634   0.066       011708.18   0.066       0
#XS Ineff= 2 , 0
       09561.601         10378.8       0
Bank Sta=9047.634,11708.18
Exp/Cntr=0.3,0.1

Type RM Length L Ch R = 1 ,5828.067,255.463200,255.463200,255.463200
XS GIS Cut Line= 3
865827.541719264769473.545199619 865986.68524381769257.545509845
866598.091436896769020.076019508
#Sta/Elev= 30
9272.33870.614069284.91169.246819345.05768.054649382.32165.887699635.37565.03011
9646.10364.636729667.55960.849599678.28760.591019699.74260.334459721.19861.53796
9753.38161.736629774.83760.791919828.47560.546269849.93159.192119892.84259.29415
9914.29858.562339946.48159.008699978.664 44.997810000.12 41.950610010.8541.50587
10021.5842.88617 10032.346.2267310043.0353.2848710053.7655.3220710085.94 57.6955
10096.6759.16582 10107.462.2321410118.1363.9539610161.0464.0440910196.5466.40738
#Mann= 3 , 0 , 0
9272.338  0.0711       09272.338  0.0711       010196.54  0.0711       0
#XS Ineff= 2 , 0
       09820.409        10116.25       0
Bank Sta=9272.338,10196.54
Exp/Cntr=0.3,0.1

Type RM Length L Ch R = 1 ,5572.604,102.655300,102.655300,102.655300
XS GIS Cut Line= 2
865961.880568203769442.505155461866659.128830807769302.789753881
#Sta/Elev= 30
9485.728 67.56279509.30767.459499519.50566.537469529.70466.850589550.10265.55296
9580.69865.344569713.28262.279149723.48162.59399 9733.6861.287389743.87962.15031
9754.07861.874249774.47560.12579 9815.27 58.27869835.66857.960929845.86756.71818
9937.65656.480529947.855 57.94599958.053 54.90049968.25246.514069978.451 42.6971
 9988.65 40.72819998.84839.9240410009.0541.2809410049.8456.1197210070.2457.24749
10080.4458.9458210090.6459.6322410121.23 58.046810141.6358.7404110196.84 58.8635
#Mann= 3 , 0 , 0
9485.728  0.0553       09485.728  0.0553       010196.84  0.0553       0
#XS Ineff= 2 , 0
       09940.348        10061.24       0
Bank Sta=9485.728,10196.84
Exp/Cntr=0.3,0.1

Type RM Length L Ch R = 3 ,5517.079,,,
BEGIN DESCRIPTION:
END DESCRIPTION:
Bridge Culvert--1,0,-1,-1, 0
Deck Dist Width WeirC Skew NumUp NumDn MinLoCord MaxHiCord MaxSubmerge Is_Ogee
20.827650,61.000000,2.6,0, 39, 39, , , 0.95, 0, 0,0,,
 9528.18 9558.68 9589.26 9609.65 9619.84 9630.04 9660.62 9670.81 9691.20 9701.39
 9711.59 9731.97 9742.17 9752.36 9762.56 9772.75 9782.94 9803.33 9823.72 9833.91
 9844.11 9854.30 9884.88 9905.27 9915.46 9925.66 9935.87 9936.73 9963.10 9963.10
10033.1010033.1010056.4310058.4310102.0310119.7110140.1410150.3510157.38
   67.30   66.44   65.31   64.23   63.78   63.09   61.65   61.05   60.05   59.50
   58.81   58.12   57.72   57.17   56.93   56.45   56.22   55.56   55.11   55.16
   55.63   56.35   59.40   61.30   62.01   62.62   63.09   62.77   62.81   62.81
   62.90   62.90   62.93   63.32   61.99   61.30   60.36   60.05   59.69
 -932.70 -933.56 -934.69 -935.77 -936.22 -936.91 -938.35 -938.95 -939.95 -940.50
 -941.19 -941.88 -942.28 -942.83 -943.07 -943.55 -943.78 -944.44 -944.89 -944.84
 -944.37 -943.65 -940.60 -938.70 -937.99 -937.38 -936.91 -937.23 -937.19   58.81
   58.90 -937.10 -937.07 -936.68 -938.01 -938.70 -939.64 -939.95 -940.31
 9528.18 9558.68 9589.26 9609.65 9619.84 9630.04 9660.62 9670.81 9691.20 9701.39
 9711.59 9731.97 9742.17 9752.36 9762.56 9772.75 9782.94 9803.33 9823.72 9833.91
 9844.11 9854.30 9884.88 9905.27 9915.46 9925.66 9935.87 9936.73 9960.31 9960.31
10030.3110030.3110056.4310058.4310102.0310119.7110140.1410150.3510157.38
   67.30   66.44   65.31   64.23   63.78   63.09   61.65   61.05   60.05   59.50
   58.81   58.12   57.72   57.17   56.93   56.45   56.22   55.56   55.11   55.16
   55.63   56.35   59.40   61.30   62.01   62.62   63.09   62.77   62.80   62.80
   62.89   62.89   62.93   63.32   61.99   61.30   60.36   60.05   59.69
 -932.70 -933.56 -934.69 -935.77 -936.22 -936.91 -938.35 -938.95 -939.95 -940.50
 -941.19 -941.88 -942.28 -942.83 -943.07 -943.55 -943.78 -944.44 -944.89 -944.84
 -944.37 -943.65 -940.60 -938.70 -937.99 -937.38 -936.91 -937.23 -937.20   58.80
   58.89 -937.11 -937.07 -936.68 -938.01 -938.70 -939.64 -939.95 -940.31
BR Coef=-1 , 0 , 0 ,, 0 ,,,0.8,0,1,0,
WSPro=,,,, 1 ,,,, 0 ,,,, 0 ,,,,-1 ,-1 ,-1 , 0 , 0 , 0 , 0 , 0
BC Design=,, 0 ,, 0 ,,,,,,

Type RM Length L Ch R = 1 ,5469.949,659.643700,659.643700,659.643700
XS GIS Cut Line= 3
866002.764723467769530.767130499866716.135279481769399.930434973
866788.249761999  769388.8509786
#Sta/Elev= 30
9506.98767.40062 9539.7667.124599651.59463.097189743.09659.251399753.262 57.8974
 9824.4356.747729834.59756.209029844.76453.598739865.09754.435829885.43157.22996
9905.76462.354039915.93162.362549926.09861.693799946.43256.417919966.76543.74144
9976.932 43.53629987.09941.5396510007.4340.2834910027.7747.6224710037.9355.90758
 10048.159.8597710058.2761.60279 10078.661.3878310098.9359.1772210119.2758.27528
 10170.157.5337210220.9455.4458310232.2655.6482810261.4658.9962210305.2260.25361
#Mann= 3 , 0 , 0
9506.987    0.04       09506.987    0.04       010305.22    0.04       0
#XS Ineff= 2 , 0
       09924.376                       0
Bank Sta=9506.987,10305.22
Exp/Cntr=0.3,0.1

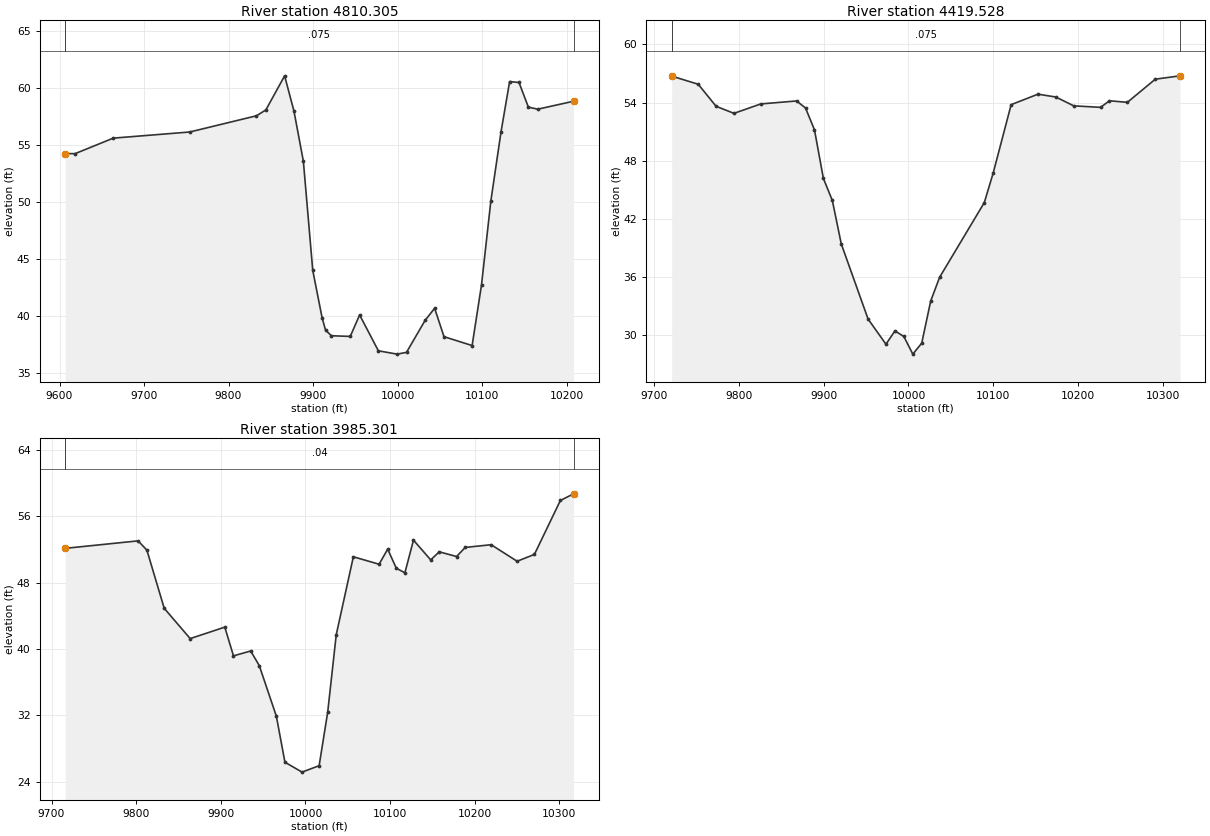
Type RM Length L Ch R = 1 ,4810.305,390.776800,390.776800,390.776800
XS GIS Cut Line= 3
867125.865320415769965.345811448867022.545933271769769.394130554
866857.824898118769426.838546399
#Sta/Elev= 30
9606.69354.259579618.38954.253759663.60955.616459754.04856.154259833.09157.57846
9844.18758.092829866.37961.085839877.47557.975869888.571 53.58299899.667 44.0077
9910.76339.837569914.85438.74993 9921.8638.268189944.05238.209459955.14840.09369
 9977.34 36.94569999.53236.6543610010.6336.8095510032.8239.6372210043.9240.67977
10055.0138.18603 10088.337.40711 10099.442.7314710110.4950.1131310122.5356.17824
10132.6860.5826210143.7860.5020910154.8858.3346810165.9758.1571510208.3258.85463
#Mann= 3 , 0 , 0
9606.693   0.075       09606.693   0.075       010208.32   0.075       0
#XS Ineff= 2 , 0
       0                               0
Bank Sta=9606.693,10208.32
Exp/Cntr=0.3,0.1

Type RM Length L Ch R = 1 ,4419.528,434.227200,434.227200,434.227200
XS GIS Cut Line= 2
867363.770292493769714.709945716867175.871519281769146.119154653
#Sta/Elev= 30
 9721.0656.74114 9752.3555.898529773.41453.625039794.47852.899199826.074 53.8715
9868.20154.175799878.73353.452629889.26551.206969899.79746.189439910.32943.91546
9920.86139.437349952.45631.68907 9973.5229.099439984.05230.471719994.58429.89605
10005.1228.0779410015.6529.2093510026.1833.5443310036.71 36.001210089.3743.70351
 10099.946.7700410120.9753.7943910152.5654.8767710173.6354.5830910194.6953.67359
10226.2953.5175610236.8254.1939210257.88 54.0356 10290.856.4205210319.8956.76795
#Mann= 3 , 0 , 0
 9721.06   0.075       0 9721.06   0.075       010319.89   0.075       0
#XS Ineff= 2 , 0
       0                               0
Bank Sta=9721.06,10319.89
Exp/Cntr=0.3,0.1

Type RM Length L Ch R = 1 ,3985.301,0.000000,0.000000,0.000000
XS GIS Cut Line= 6
867736.585988518769578.179377236867711.394749899769484.896061181
867687.563477592769373.004837597  867666.5392783769229.317824231
867650.313173719769139.115458451867618.699791612 768989.82049512
#Sta/Elev= 30
9716.18552.150379802.344 53.05289812.702 51.92869833.15244.922369863.82541.27073
9904.72242.652449914.94639.192369935.305 39.77459945.41638.019749965.63931.91252
 9975.7526.369589995.973 25.173410016.1725.9491610026.2832.4026610036.3841.74244
10056.5951.1327510086.9850.2357710097.1452.05472 10107.349.7607310117.46 49.1985
10127.6253.1387410147.9450.76116 10158.1 51.7292 10178.551.1655110188.7252.25956
10219.38 52.588810250.0450.5939910270.4851.4201510301.1457.9192810316.6958.72292
#Mann= 3 , 0 , 0
9716.185    0.04       09716.185    0.04       010316.69    0.04       0
#XS Ineff= 2 , 0
       0                               0
Bank Sta=9716.185,10316.69
Exp/Cntr=0.3,0.1